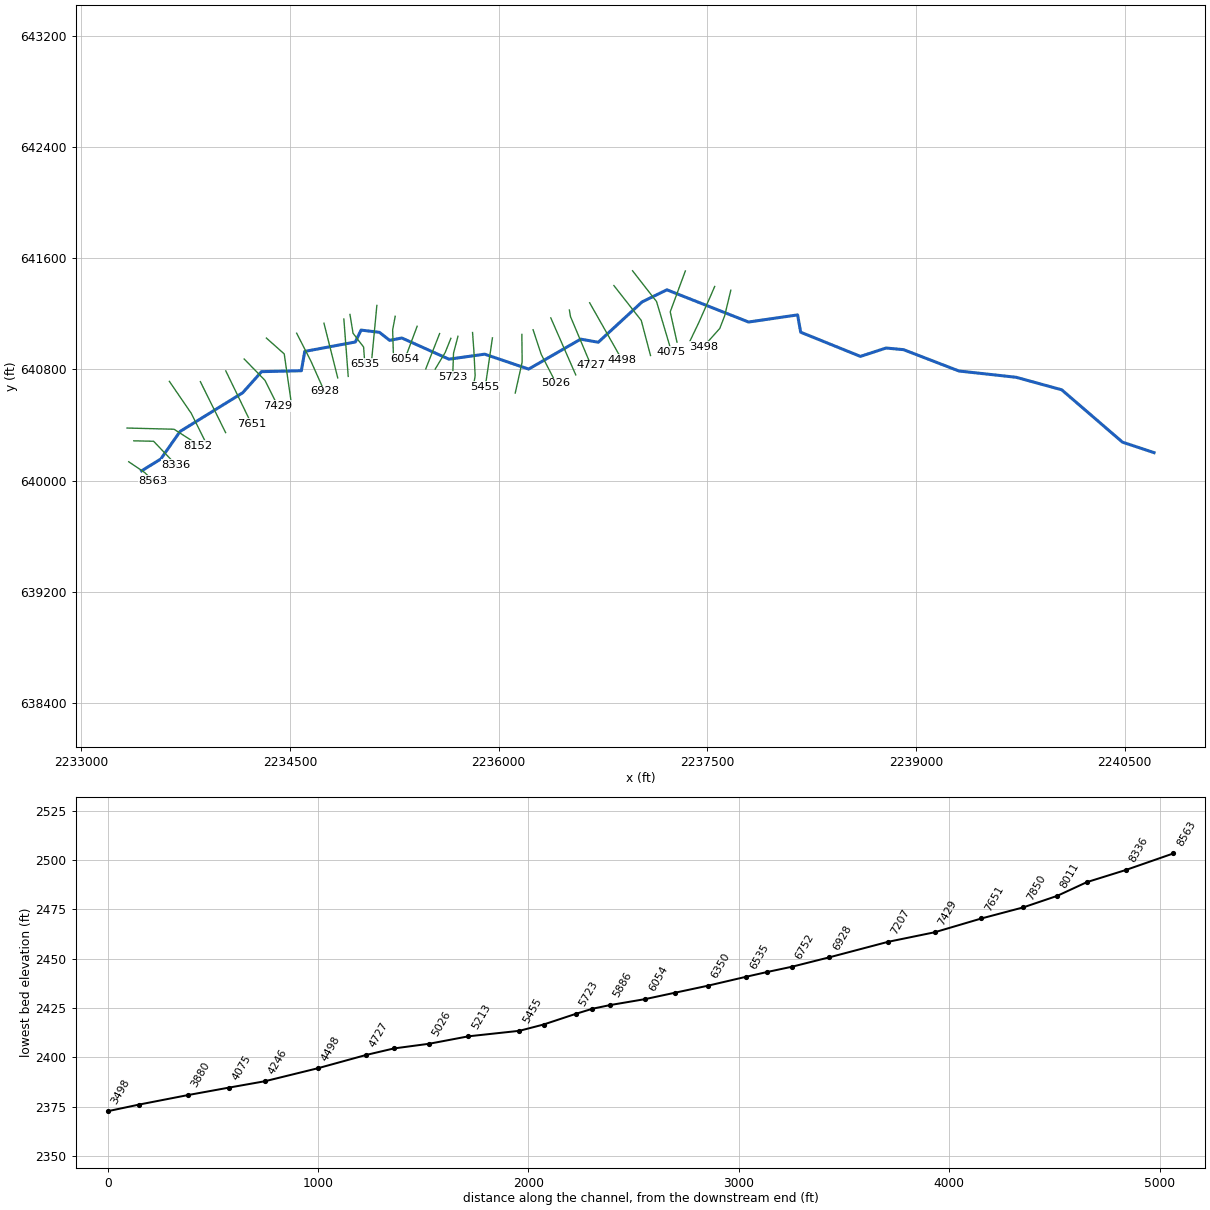
--- SCHOOLCRN.prj (project) ---

Proj Title=SCHOOLCRN
Current Plan=p01
Default Exp/Contr=0,0
English Units
Geom File=g01
Flow File=f01
Plan File=p01
BEGIN DESCRIPTION:
----------MODEL BY WOOD PLC 2022----------
AFH study:SCHOOLCRN
Randolph County, WV
HEC-RAS Version: RAS 6.2
Vertical Datum: NAVD88
Projection: NAD 1983 StatePlane West Virginia S FIPS 4702 (US Feet)
Terrain: 1-meter LIDAR (FEMA Region III 3DEP collected 2016-2018)
Land Use: 2019 NLCD
Hydrologic Method:
WV SIR2010-5033 regression equations
Additional Model Notes:
None
END DESCRIPTION:
DSS Export Rating Curves= 0
DSS Export Rating Curve Sorted= 0
DSS Export Volume Flow Curves= 0
DXF OffsetX= 0
DXF OffsetY= 0
DXF ScaleX= 0
DXF ScaleY= 0

--- SCHOOLCRN.p01 (plan) ---

Plan Title=Floodplain
Program Version=6.20
Short Identifier=Floodplain
Geom File=g01
Flow File=f01
Subcritical Flow
K Sum by GR= 0
Std Step Tol= 0.01
Critical Tol= 0.01
Num of Std Step Trials= 20
Max Error Tol= 0.3
Flow Tol Ratio= 0.001
Split Flow NTrial= 30
Split Flow Tol= 0.02
Split Flow Ratio= 0.02
Log Output Level= 0
Friction Slope Method= 1
Unsteady Friction Slope Method= 2
Unsteady Bridges Friction Slope Method= 1
Parabolic Critical Depth
Global Vel Dist= 0 , 0 , 0
Global Log Level= 0
CheckData=True
Encroach Param=-1 ,0,0, 0
Mapping Interval=1HOUR
Computation Time Step Use Courant=        0
Computation Time Step Use Time Series=    0
Computation Time Step Count To Double=0
Computation Time Step Max Doubling=0
Computation Time Step Max Halving=0
Computation Time Step Residence Courant=0
Run HTab= 0
Run UNet= 0
Run Sediment= 0
Run PostProcess= 0
Run WQNet= 0
Run RASMapper=-1
UNET Theta= 0
UNET Theta Warmup= 0
UNET ZTol= 0
UNET ZSATol= 0
UNET MxIter= 0
UNET Max Iter WO Improvement= 0
UNET MaxInSteps= 0
UNET DtIC= 0
UNET DtMin= 0
UNET MaxCRTS= 0
UNET WFStab= 0
UNET SFStab= 0
UNET WFX= 1
UNET SFX= 1
UNET Gravity=32.174
UNET 1D Methodology=Finite Difference
UNET DSS MLevel= 1
UNET Pardiso=0
UNET DZMax Abort= 0
UNET Use Existing IB Tables= 0
UNET Froude Reduction=False
UNET Froude Limit= 0
UNET Froude Power= 0
UNET D1 Cores= 0
UNET WindReference=Eulerian
UNET WindDragFormulation=Hsu (1988)
UNET D2 Coriolis=0
UNET D2 Cores= 0
UNET D2 Theta= 1
UNET D2 Theta Warmup= 1
UNET D2 Z Tol= 0.01
UNET D2 Volume Tol= 0.01
UNET D2 Max Iterations= 20
UNET D2 Equation= 0
UNET D2 RampUpFraction=0.1
UNET D2 TimeSlices= 1
UNET D2 Turbulence Formulation=Non-Conservative (original)
UNET D2 Eddy Viscosity=0.3
UNET D2 Transverse Eddy Viscosity=0.1
UNET D2 Smagorinsky Mixing=0
UNET D2 BCVolumeCheck=0
UNET D2 Cores=0
UNET D2 SolverType=PARDISO (Direct)
UNET D2 Minimum Iterations= 2147483647
UNET D2 Maximum Iterations= 2147483647
UNET D2 Restart Number= 10
UNET D2 Relaxation Coeff=1.3
UNET D2 SOR Precondition Iterations= 10
UNET D2 ILUT Maximum Fill= 8
UNET D2 ILUT Tolerance=1E-08
UNET D1D2 MaxIter= 0
UNET D1D2 ZTol=0.01
UNET D1D2 QTol=0.1
UNET D1D2 MinQTol=1
Write IC File= 0
Write IC File at Fixed DateTime=0
Write IC File at Sim End=0
Echo Input=False
Echo Parameters=False
Echo Output=False
Write Detailed= 0
HDF Write Warmup=0
HDF Write Time Slices=0
HDF Flush=0
HDF Compression= 1
HDF Chunk Size= 1
HDF Spatial Parts= 1
HDF Use Max Rows=0
HDF Fixed Rows= 1
Calibration Method= 0
Calibration Iterations= 20
Calibration Max Change=0.05
Calibration Tolerance=0.2
Calibration Maximum=1.5
Calibration Minimum=0.5
Calibration Optimization Method= 1
WQ AD Non Conservative
WQ ULTIMATE=-1
WQ Max Comp Step=1HOUR
WQ Output Interval=15MIN
WQ Output Selected Increments= 0
WQ Output face flow=0
WQ Output face velocity=0
WQ Output face area=0
WQ Output face dispersion=0
WQ Output cell volume=0
WQ Output cell surface area=0
WQ Output cell continuity=0
WQ Output cumulative cell continuity=0
WQ Output face conc=0
WQ Output face dconc_dx=0
WQ Output face courant=0
WQ Output face peclet=0
WQ Output face adv mass=0
WQ Output face disp mass=0
WQ Output cell mass=0
WQ Output cell source sink temp=0
WQ Output nsm pathways=0
WQ Output nsm derived pathways=0
WQ Create Restart=0
WQ Fixed Restart=0
WQ System Summary=0
WQ Write To DSS=0
Sorting and Armoring Iterations= 10
XS Update Threshold= 0.02
Bed Roughness Predictor= 0
Hydraulics Update Threshold= 0.02
Energy Slope Method= 1
Volume Change Method= 1
Sediment Retention Method= 0
Sediment TS Multiplier= 1
Warm Up Method= 0
XS Weighting Method= 0
Number of US Weighted Cross Sections= 1
Number of DS Weighted Cross Sections= 1
Upstream XS Weight=0
Main XS Weight=1
Downstream XS Weight=0
Number of DS XS's Weighted with US Boundary= 1
Upstream Boundary Weight= 1
Weight of XSs Associated with US Boundary= 0
Number of US XS's Weighted with DS Boundary= 1
Downstream Boundary Weight= 0.5
Weight of XSs Associated with DS Boundary= 0.5
Percentile Method= 0
Sediment Output Level= 3
Mass or Volume Output= 0
Output Increment Type= 1
Profile and TS Output Increment= 1
Transport Output Increment 1
XS Output Flag= 0
XS Output Increment= 10
Read HDF5 Sediment Hotstart= 0
Sediment Hotstart Type= 0
Write Gradation File= 0
Read Gradation Hotstart= 0
Write HDF5 File= 1
Write Binary Output= 1
Write DSS Sediment File= 0
DSS Sediment Output Type= 1
SV Curve= 0
Specific Gage Flag= 0
Subcell Erosion Methods= 0
Subcell Deposition Methods= 0
Advection Scheme= 1
Matrix Solver= 0
Implicit Weighting Factor= 1
Maximum Outer Loop Convergence Iterations= 5
Convergence Maximum Absolute= 0.001
Convergence RMSE= 0.0001
Grain Fractions Max Abs Error= 0.001
Max Subgrid Regions= 1
Max Subgrid Length Scale= 3.402823E+38
Initial Layer Thickness= 3.402823E+38
Min Layer Thickness= 3.402823E+38
Max Layer Thickness= 3.402823E+38
Number of Layers= 5

--- SCHOOLCRN.f01 (steady flow) ---

Flow Title=Flow
Program Version=6.20
Number of Profiles= 1
Profile Names=P100yr
River Rch & RM=SCHOOLCRN,Main            ,8563
     654
River Rch & RM=SCHOOLCRN,Main            ,3365
     753
Boundary for River Rch & Prof#=SCHOOLCRN,Main            , 1
Up Type= 0
Dn Type= 3
Dn Slope=0.03659
DSS Import GetInterval= 0
DSS Import GetPeak= 0
DSS Import FillOption= 0

--- SCHOOLCRN.g01 (geometry) ---

Geom Title=Geometry
Program Version=6.20

River Reach=SCHOOLCRN       ,Main
Reach XY= 30
     2233432.243      640070.012     2233570.368      640155.169
2233708.70406837640353.065331445     2234159.123      640631.475
     2234294.847      640783.293     2234581.003      640789.881
     2234605.405      640928.835     2234969.104       640996.61
     2235010.221      641082.139     2235142.243      641066.106
     2235216.201      641008.294     2235303.448      641025.352
     2235642.332      640872.908     2235899.038      640909.085
     2236215.509      640801.8632236589.58015158641017.120657767
2236716.04892087640994.755006675     2237031.314      641285.046
     2237209.472      641371.769     2237796.666      641140.225
2238149.24769543641191.384027754     2238171.521      641066.843
     2238600.983      640893.0732238785.44164199640953.200158979
2238911.11846774640941.463106208     2239309.143      640788.074
2239720.62424731640742.8544166672240048.52476985640652.785071731
2240485.40657067640276.281167641     2240712.485      640200.935

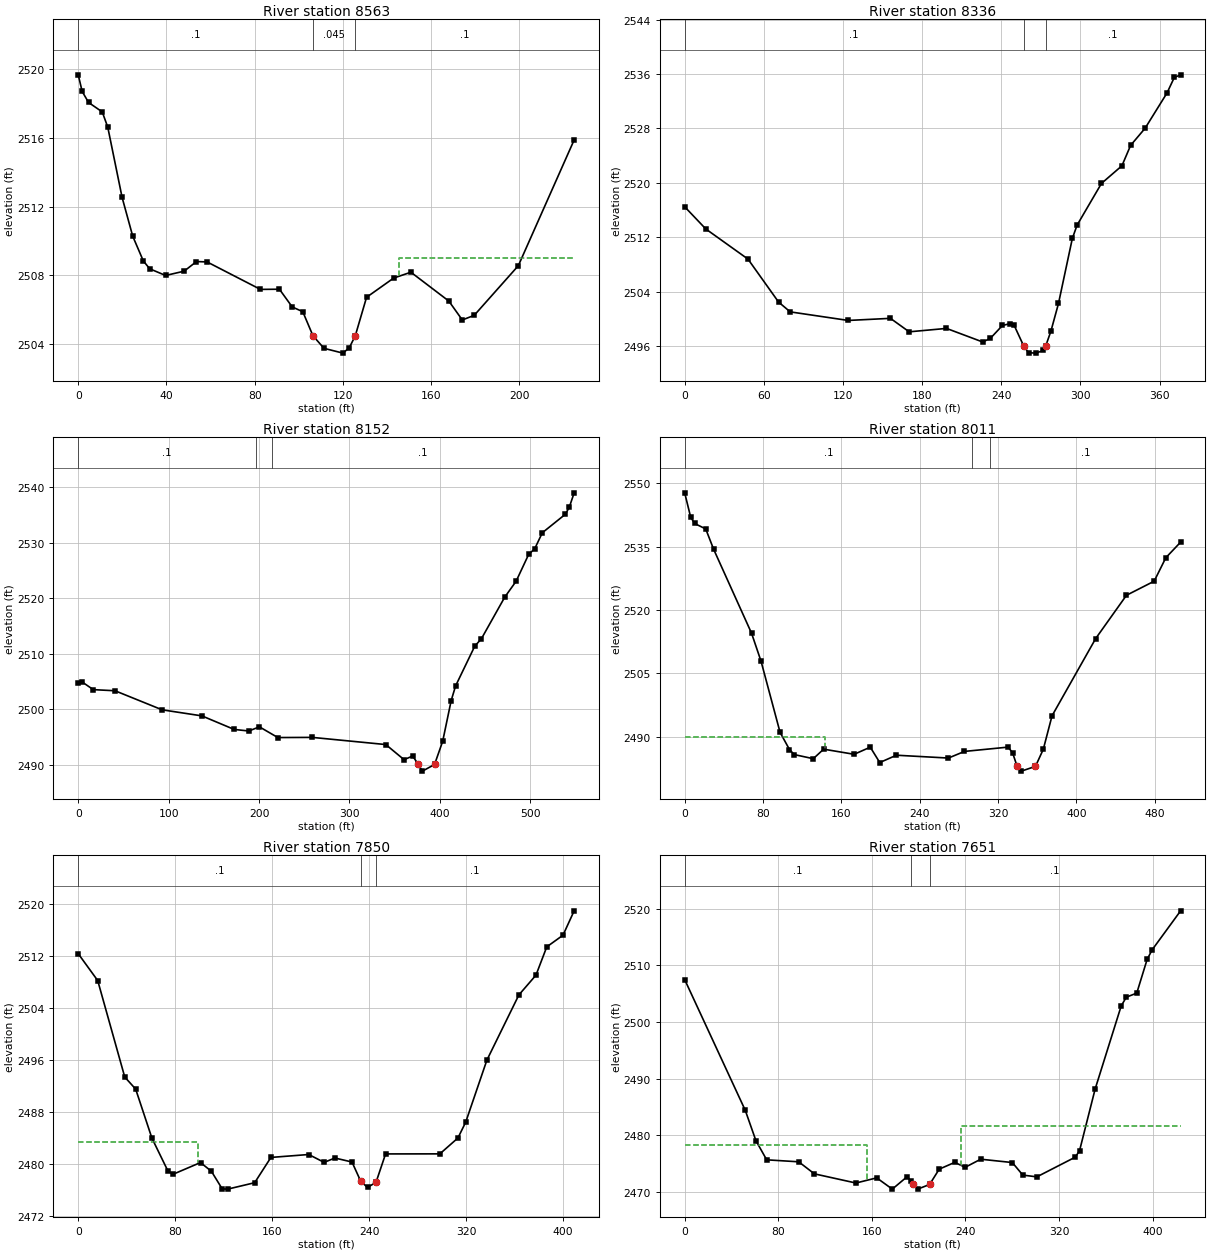
Type RM Length L Ch R = 1 ,8563    ,227.5,227.8,222
XS GIS Cut Line= 3
2233339.66084542640135.2315631052233452.75144307640059.356082252
2233516.34232226 639997.57176213
#Sta/Elev= 30
       0 2519.67     1.8  2518.7     4.7 2518.06    10.9 2517.51    13.4 2516.62
    19.9 2512.53    24.7 2510.28    29.5 2508.84    32.4 2508.38    39.6 2507.99
      48 2508.24    53.6  2508.8    58.4 2508.78    82.6 2507.18    91.2 2507.19
      97 2506.16   101.8 2505.88   106.42504.483   111.4 2503.75     120 2503.47
   122.9 2503.79   125.62504.484   130.7 2506.72     143 2507.84   150.8 2508.18
     168  2506.5   174.1  2505.4   179.5 2505.67   199.5 2508.56   224.8 2515.88
#Mann= 3 ,-1,0
       0      .1       0   106.4    .045       0   125.6      .1       0
#XS Ineff= 2 , 0
                          145.42         2509.01
Permanent Ineff=
       F       F
Bank Sta=106.4,125.6
XS Rating Curve= 0 ,0
Exp/Cntr(USF)=0,0
Exp/Cntr=0.3,0.1

Type RM Length L Ch R = 1 ,8336    ,181.7,183.9,185.7
XS GIS Cut Line= 3
2233376.16622488640285.9662699392233518.68366246640282.754609374
2233679.66814829640113.740972131
#Sta/Elev= 30
       0  2516.5      16 2513.24      48 2508.81    71.2  2502.5      80 2501.06
     124  2499.8     156 2500.11   170.2 2498.13   198.5 2498.63   225.9 2496.64
   231.7 2497.16   240.9 2499.06   246.6 2499.33   249.7 2499.12     2572496.063
   260.7 2495.06   266.3    2495   271.8 2495.39   273.72496.041   277.7 2498.25
   283.4 2502.29   293.9 2511.84   297.5  2513.8     316 2519.93   331.5 2522.52
   338.1 2525.52   349.1 2528.04   365.7 2533.22   371.2 2535.49     376 2535.88
#Mann= 3 ,-1,0
       0      .1       0     257    .045       0   273.7      .1       0
Bank Sta=257,273.7
XS Rating Curve= 0 ,0
Exp/Cntr(USF)=0,0
Exp/Cntr=0.3,0.1

Type RM Length L Ch R = 1 ,8152    ,144.3,140.6,134.6
XS GIS Cut Line= 4
2233327.44541503640377.8837534382233665.45606486640369.268642195
2233783.30053117640293.727317637 2233838.4456981640249.913349393
#Sta/Elev= 30
       0  2504.8     4.7 2504.88    16.7 2503.54    40.7 2503.34    92.8 2499.91
   136.8 2498.82   172.5 2496.38   188.7  2496.1   200.4 2496.85   220.8 2494.92
   258.9 2494.95   340.2 2493.66   360.4 2490.94   369.9  2491.6   376.12490.096
   380.7 2488.88   394.12490.076   403.1 2494.25   412.5 2501.58   417.4 2504.22
   438.6 2511.37   445.9 2512.69   471.7 2520.17   484.3 2523.04   498.3 2527.91
   504.8 2528.86   513.3 2531.77   538.9 2535.11   543.3 2536.44   548.5 2538.95
#Mann= 3 ,-1,0
       0      .1       0   196.5    .045       0   214.5      .1       0
Bank Sta=376.1,394.1
XS Rating Curve= 0 ,0
Exp/Cntr(USF)=0,0
Exp/Cntr=0.3,0.1

Type RM Length L Ch R = 1 ,8011    ,160.8,160.9,160.8
XS GIS Cut Line= 3
2233632.01408025640713.508905658 2233788.8721724640484.394815688
2233890.85296056640279.677826134
#Sta/Elev= 30
       0 2547.71     6.1 2541.97    10.1 2540.47    21.5 2539.17    29.5  2534.4
    68.3 2514.51      78 2507.88    97.4 2491.08     107 2487.03   111.9 2485.83
   131.3 2484.86   141.9 2487.11     173  2485.9   189.5 2487.58   199.2 2483.95
   216.2 2485.68   269.3 2485.01   285.7 2486.58   330.4  2487.6   334.9  2486.2
   339.5 2483.02   343.8 2481.92   358.22483.047   366.2  2487.1   375.1    2495
   419.7 2513.27   451.1 2523.49   479.4 2526.82   491.3 2532.37   506.4 2536.05
#Mann= 3 ,-1,0
       0      .1       0   293.2    .045       0   311.9      .1       0
#XS Ineff= 2 , 0
          143.13 2490.03
Permanent Ineff=
       F       F
Bank Sta=339.5,358.2
XS Rating Curve= 0 ,0
Exp/Cntr(USF)=0,0
Exp/Cntr=0.3,0.1

Type RM Length L Ch R = 1 ,7850    ,199.2,199.2,198.6
XS GIS Cut Line= 2
2233854.74392942640711.6246040092234036.38566565640344.987179543
#Sta/Elev= 30
       0 2512.41    16.1 2508.26    38.4 2493.38    47.4 2491.52    60.8 2483.96
    74.2 2478.82    78.6 2478.41   100.9 2480.19   109.9 2478.84   118.8 2476.13
   123.3 2476.09   145.6 2477.08     159 2480.98   190.2 2481.43   202.9 2480.22
   211.8 2480.89   225.9 2480.27   233.22477.267   238.7 2476.36   245.72477.128
   253.6 2481.52   298.4 2481.53   313.3 2483.98   319.7 2486.41   337.2 2495.99
   363.6 2506.05   377.7  2509.1   386.6 2513.46     400 2515.26   409.2 2519.02
#Mann= 3 ,-1,0
       0      .1       0   233.2    .045       0   245.7      .1       0
#XS Ineff= 2 , 0
           99.19 2483.42
Permanent Ineff=
       F       F
Bank Sta=233.2,245.7
XS Rating Curve= 0 ,0
Exp/Cntr(USF)=0,0
Exp/Cntr=0.3,0.1

Type RM Length L Ch R = 1 ,7651    ,220,222.1,224.9
XS GIS Cut Line= 2
2234037.58550706640788.9144333932234222.66175223640407.430744371
#Sta/Elev= 30
       0  2507.5    51.8 2484.38    60.9 2479.02    70.1 2475.63    97.5 2475.28
   110.9 2473.15   146.4 2471.53   164.2 2472.44   177.5 2470.45   190.3 2472.67
   193.62471.824   195.3 2471.34   199.8  2470.5   209.42471.273   217.6 2473.98
   230.9 2475.18   239.8 2474.31   253.1 2475.74   280.1 2475.15   289.1 2472.93
   301.1 2472.62     334 2476.11   337.6 2477.26   350.9 2488.13   373.2 2502.84
   377.6 2504.39   386.5  2505.1   395.4 2511.08   399.8  2512.8     424 2519.65
#Mann= 3 ,-1,0
       0      .1       0   193.6    .045       0   209.4      .1       0
#XS Ineff= 2 , 0
          155.84 2478.21  236.57         2481.56
Permanent Ineff=
       F       F
Bank Sta=195.3,209.4
XS Rating Curve= 0 ,0
Exp/Cntr(USF)=0,0
Exp/Cntr=0.3,0.1

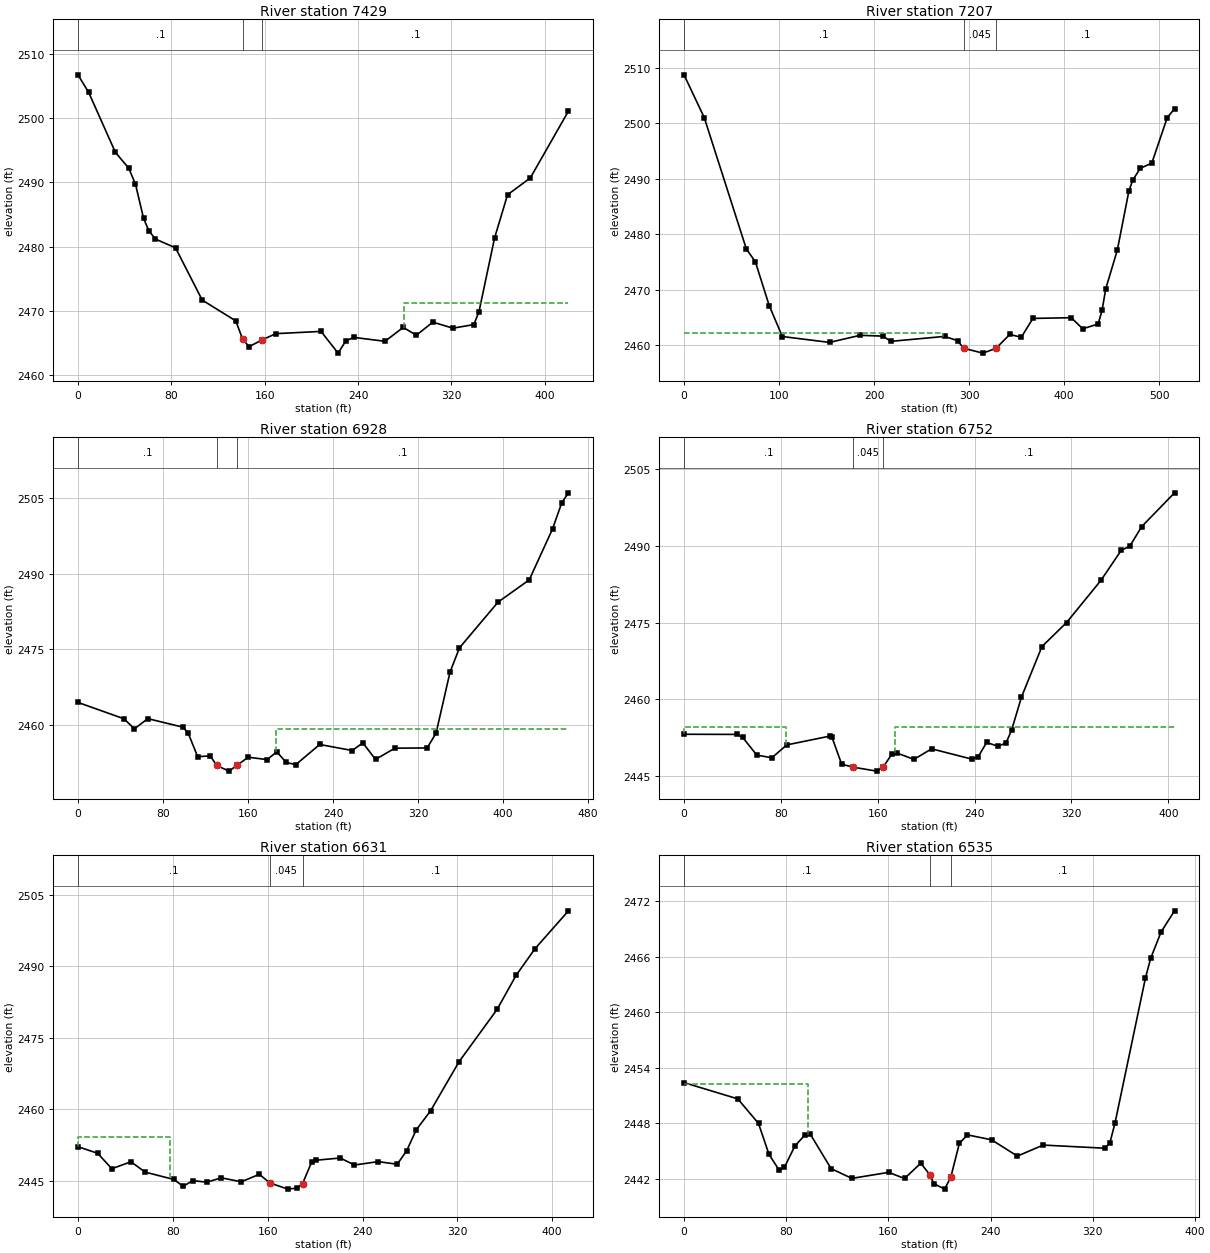
Type RM Length L Ch R = 1 ,7429    ,221.7,221.7,215.4
XS GIS Cut Line= 3
2234169.78282504640874.2761301442234319.35464766 640720.92724129
2234411.51506363640536.606409367
#Sta/Elev= 30
       0 2506.74     9.2 2504.01    32.1 2494.67    43.5 2492.23    49.3 2489.73
    56.2 2484.44    60.7  2482.5    66.4 2481.19    83.6 2479.83   106.5  2471.7
   135.2 2468.47   141.2 2465.59   146.7 2464.46   158.1 2465.54   169.6 2466.48
   208.3 2466.83   222.9 2463.45   229.5 2465.34   236.3  2465.9   263.1 2465.29
   278.7 2467.45     290 2466.24   304.1 2468.27   321.3 2467.33   339.2 2467.89
   343.6 2469.87     357 2481.37   368.1 2488.08   387.6  2490.7   420.3  2501.1
#Mann= 3 ,-1,0
       0      .1       0   141.2    .045       0   158.1      .1       0
#XS Ineff= 2 , 0
                          279.37         2471.18
Permanent Ineff=
       F       F
Bank Sta=141.2,158.1
XS Rating Curve= 0 ,0
Exp/Cntr(USF)=0,0
Exp/Cntr=0.3,0.1

Type RM Length L Ch R = 1 ,7207    ,256.2,279,282.1
XS GIS Cut Line= 3
2234329.66759352641024.740027496 2234457.8963802640910.758218541
2234507.14406205640569.576530058
#Sta/Elev= 30
       0 2508.71    21.3 2501.01    65.6 2477.35    75.1 2475.04    89.7 2467.14
   103.5 2461.58   153.2 2460.52   185.3  2461.8   209.5 2461.65   217.6 2460.71
   274.2  2461.6     288 2460.84   294.22459.476   314.6 2458.59   328.42459.458
   342.9 2461.96     355 2461.44   367.2 2464.84   407.6 2464.97   419.7 2462.97
   435.9 2463.84     440 2466.27   443.9 2470.17   456.1 2477.15   468.2 2487.73
   472.2 2489.72   480.3 2491.88   492.4 2492.81   508.6 2500.99   516.3  2502.6
#Mann= 3 ,-1,0
       0      .1       0   294.2    .045       0   328.4      .1       0
#XS Ineff= 2 , 0
          272.47 2462.25
Permanent Ineff=
       F       F
Bank Sta=294.2,328.4
XS Rating Curve= 0 ,0
Exp/Cntr(USF)=0,0
Exp/Cntr=0.3,0.1

Type RM Length L Ch R = 1 ,6928    ,179.2,176.5,174.8
XS GIS Cut Line= 3
2234547.22824057641059.7006644562234649.20902872640860.271567621
2234745.90192416640643.467966138
#Sta/Elev= 30
       0  2464.4    43.3 2461.14    53.1 2459.14    65.7 2461.17    98.7 2459.48
   103.6 2458.34   112.6 2453.61   124.5 2453.75   130.52451.856   142.1 2450.73
   149.62451.863   160.1  2453.5     178 2453.02     187 2454.57     196 2452.45
     205 2452.03   227.4 2456.03     258 2454.83     268 2456.35   279.9 2453.06
   298.2  2455.3   328.5 2455.34   336.9 2458.31     350 2470.44   358.9 2475.26
   395.2 2484.36   424.5 2488.77   446.4 2498.89   455.1 2504.12   461.4 2506.09
#Mann= 3 ,-1,0
       0      .1       0   130.5    .045       0   149.6      .1       0
#XS Ineff= 2 , 0
                          186.55          2459.2
Permanent Ineff=
       F       F
Bank Sta=130.5,149.6
XS Rating Curve= 0 ,0
Exp/Cntr(USF)=0,0
Exp/Cntr=0.3,0.1

Type RM Length L Ch R = 1 ,6752    ,123.9,121.3,119.9
XS GIS Cut Line= 2
2234743.63568442641131.4649227862234842.59481959640738.650035082
#Sta/Elev= 30
       0 2453.19    43.6 2453.16    48.5 2452.56    60.1 2449.12    72.5 2448.59
    84.9 2451.11   120.9 2452.85     122 2452.74   130.2 2447.34   139.62446.758
   159.1 2445.98   164.52446.776   171.5 2449.26   175.6 2449.54   189.9 2448.28
   204.5 2450.34   237.5 2448.34   242.9 2448.77   249.9 2451.58   259.3 2450.85
   265.9 2451.47   270.5 2453.96   278.7 2460.47   295.6 2470.34   315.9 2475.03
   344.3 2483.28   361.2  2489.2   368.1 2489.94   377.9 2493.78   405.1 2500.41
#Mann= 3 ,-1,0
       0      .1       0   139.6    .045       0   164.5      .1       0
#XS Ineff= 2 , 0
           83.95  2454.6  174.11         2454.69
Permanent Ineff=
       F       F
Bank Sta=139.6,164.5
XS Rating Curve= 0 ,0
Exp/Cntr(USF)=0,0
Exp/Cntr=0.3,0.1

Type RM Length L Ch R = 1 ,6631    ,90.3,96,101.5
XS GIS Cut Line= 2
 2234886.6363336641161.7105936072234917.95453372640749.150902466
#Sta/Elev= 30
       0 2452.12    16.6 2450.74    28.6  2447.5    44.7 2448.96    56.7 2446.79
    80.8 2445.25    88.8 2443.82    96.8    2445   108.8 2444.68   120.9 2445.59
   137.8 2444.76     153 2446.33   161.82444.526     177 2443.22   185.1 2443.46
   189.42444.357   197.1 2448.89   201.1 2449.29   221.2 2449.75   233.2 2448.28
   253.3 2448.99   269.3 2448.44   277.3  2451.3   285.3 2455.65   297.4 2459.65
   321.5 2469.98   353.5 2480.92   369.6  2488.1   385.6  2493.7   413.7 2501.61
#Mann= 3 ,-1,0
       0      .1       0   161.8    .045       0   189.4      .1       0
#XS Ineff= 2 , 0
           78.01 2454.25
Permanent Ineff=
       F       F
Bank Sta=161.8,189.4
XS Rating Curve= 0 ,0
Exp/Cntr(USF)=0,0
Exp/Cntr=0.3,0.1

Type RM Length L Ch R = 1 ,6535    ,186.8,184.6,172.9
XS GIS Cut Line= 4
2234930.58190379641194.7674336362234952.60975403641059.540908543
2235028.48346041640960.4155824572235037.66173135640838.650521401
#Sta/Elev= 30
       0 2452.41    42.1 2450.65    58.3    2448    66.5 2444.66    74.6 2442.92
    78.6 2443.26    86.7 2445.54    94.8 2446.78    98.9 2446.82   115.1 2443.12
   131.3 2442.06   160.1 2442.71   172.6 2442.05   185.3  2443.7   192.6 2442.42
   195.4  2441.5     204  2440.9   208.82442.198   215.5 2445.84   221.8 2446.76
   240.7 2446.23   260.9 2444.47   281.1 2445.66   329.3 2445.32   333.3 2445.89
   337.3 2448.03   361.1 2463.69   365.3 2465.87   373.4 2468.69   383.9 2470.97
#Mann= 3 ,-1,0
       0      .1       0   192.6    .045       0   208.8      .1       0
#XS Ineff= 2 , 0
              97 2452.22
Permanent Ineff=
       F       F
Bank Sta=192.6,208.8
XS Rating Curve= 0 ,0
Exp/Cntr(USF)=0,0
Exp/Cntr=0.3,0.1

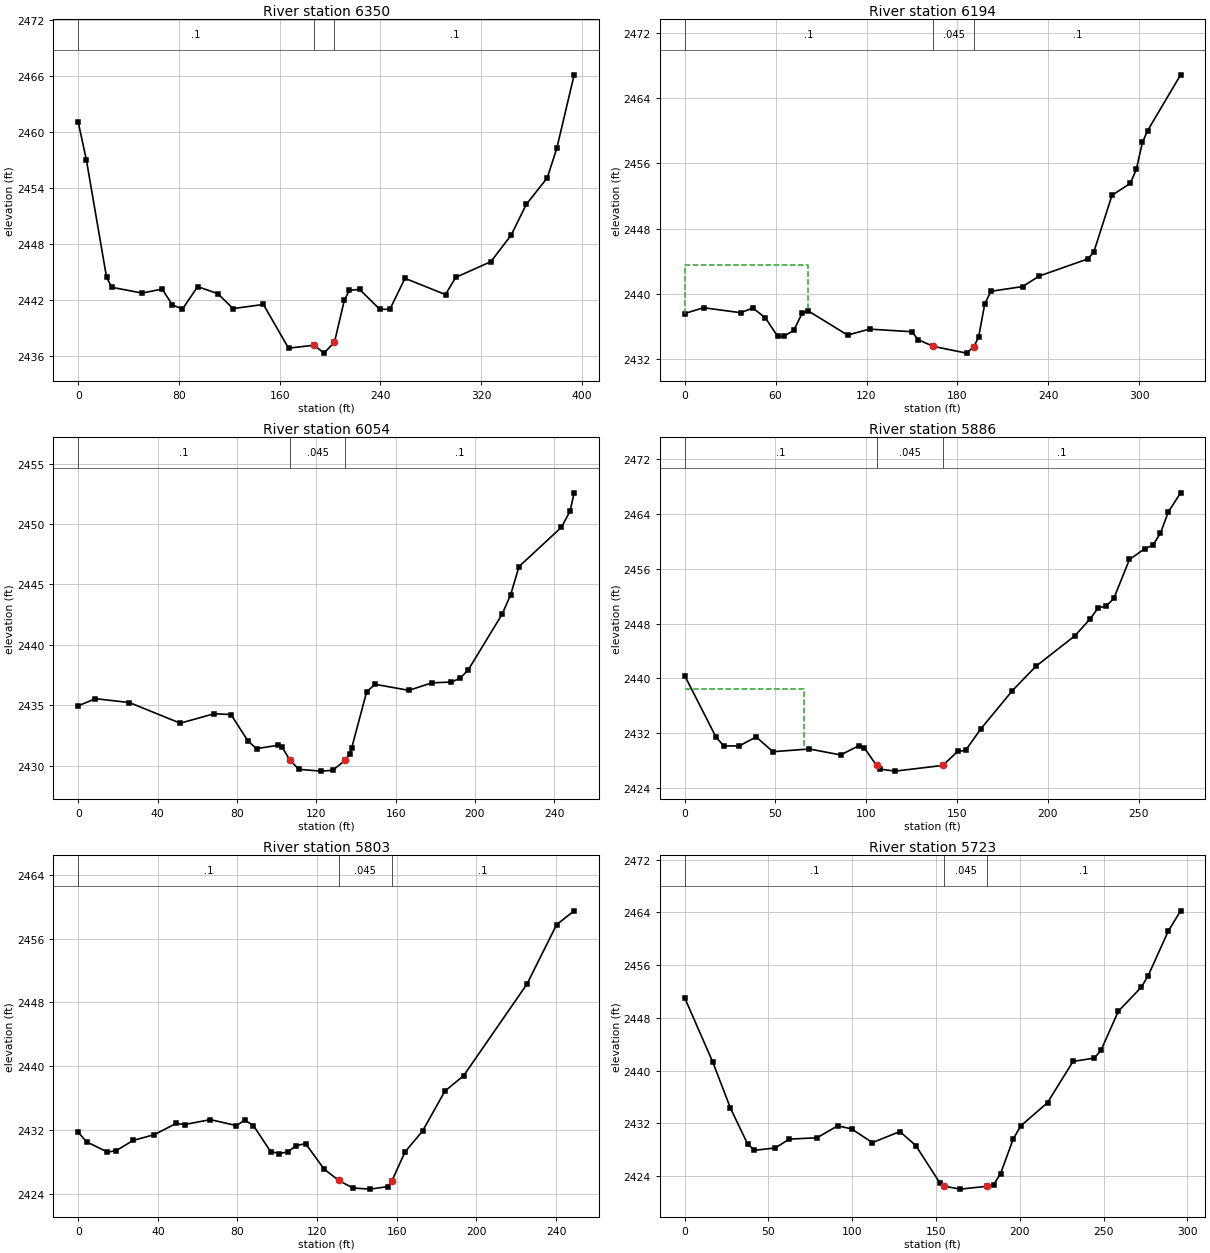
Type RM Length L Ch R = 1 ,6350    ,152.3,155.5,160
XS GIS Cut Line= 2
2235123.93747813641259.6272149022235086.61250966640867.409103661
#Sta/Elev= 30
       0 2461.02     6.5 2456.97    22.5 2444.42    26.6 2443.34    50.7 2442.72
    66.7 2443.15    74.8 2441.46    82.8 2441.01    94.9 2443.41   110.9 2442.66
     123 2441.06   147.1  2441.5   167.1 2436.82   187.3 2437.14   195.3 2436.29
   203.62437.475   211.4 2441.95   215.4 2443.01   223.5 2443.12   239.5 2440.99
   247.6 2440.98   259.6  2444.3   291.8 2442.56   299.8 2444.39   327.9 2446.09
     344 2448.94     356 2452.22   372.6 2455.05   380.2 2458.22     394 2466.09
#Mann= 3 ,-1,0
       0      .1       0   187.3    .045       0   203.6      .1       0
Bank Sta=187.3,203.6
XS Rating Curve= 0 ,0
Exp/Cntr(USF)=0,0
Exp/Cntr=0.3,0.1

Type RM Length L Ch R = 1 ,6194    ,145.2,140.2,134.5
XS GIS Cut Line= 3
2235255.85007059641181.4493115942235237.49352873641082.935870237
2235244.22426074640855.926635806
#Sta/Elev= 30
       0  2437.6    12.5 2438.31    36.9  2437.7      45 2438.27    53.2 2437.08
    61.3 2434.82    65.4 2434.81      72 2435.54    77.6 2437.67    81.7  2437.9
   107.5 2434.96     122 2435.69     150 2435.37     154  2434.4   164.12433.578
     186 2432.75  190.96 2433.56     194 2434.73     198 2438.74     202 2440.32
     223  2440.9     234 2442.19     266 2444.28     270 2445.13     282 2452.08
   294.1 2453.54   298.1 2455.28   302.1 2458.56   305.5 2459.99   327.3 2466.83
#Mann= 3 ,0,0
       0      .1       0   164.1    .045       0  190.96      .1       0
#XS Ineff= 2 , 0
           81.71 2443.57
Permanent Ineff=
       F       F
Bank Sta=164.1,190.96
XS Rating Curve= 0 ,0
Exp/Cntr(USF)=0,0
Exp/Cntr=0.3,0.1

Type RM Length L Ch R = 1 ,6054    ,168.7,168.3,167.8
XS GIS Cut Line= 2
 2235413.3989007641109.3371696162235325.80189109640875.186013505
#Sta/Elev= 30
       0 2434.95     8.7 2435.54    25.8 2435.22    51.4 2433.51    68.5 2434.29
      77 2434.23    85.6 2432.03    89.9  2431.4   100.5 2431.68   102.7 2431.54
   106.72430.456   111.2 2429.69   122.3 2429.54   128.3 2429.61   134.62430.443
   136.8 2430.92   137.8 2431.42   145.4 2436.11   149.6 2436.73   166.7 2436.23
   178.2 2436.85   188.1 2436.92   192.4 2437.22   196.6 2437.92   213.7 2442.54
     218 2444.15   222.2 2446.48   243.6 2449.74   247.9 2451.06     250 2452.59
#Mann= 3 ,-1,0
       0      .1       0   106.7    .045       0   134.6      .1       0
Bank Sta=106.7,134.6
XS Rating Curve= 0 ,0
Exp/Cntr(USF)=0,0
Exp/Cntr=0.3,0.1

Type RM Length L Ch R = 1 ,5886    ,88.3,83.4,81.1
XS GIS Cut Line= 2
2235575.25492496641057.1584657322235475.31375257640802.886367267
#Sta/Elev= 30
       0 2440.41    17.2 2431.47    21.5 2430.15    30.1 2430.16    39.4 2431.47
    48.6 2429.31    68.7 2429.71    85.9 2428.84    95.9 2430.18    98.8 2429.92
   105.72427.313   107.4 2426.78     116 2426.48   142.22427.314   150.4 2429.36
   154.7  2429.5   163.3 2432.69   180.5 2438.21   193.4 2441.75   214.9  2446.2
   223.5 2448.71   227.8 2450.31   232.1 2450.52   236.4 2451.66     245 2457.34
   253.6 2458.94   257.9 2459.41   262.1 2461.18   266.4 2464.26   273.2 2467.06
#Mann= 3 ,-1,0
       0      .1       0   105.7    .045       0   142.2      .1       0
#XS Ineff= 2 , 0
            65.8 2438.47
Permanent Ineff=
       F       F
Bank Sta=105.7,142.2
XS Rating Curve= 0 ,0
Exp/Cntr(USF)=0,0
Exp/Cntr=0.3,0.1

Type RM Length L Ch R = 1 ,5803    ,73.7,79.8,87.9
XS GIS Cut Line= 3
2235656.02666543 641022.831103082235615.07799322640920.860880135
2235543.21708807640801.627981651
#Sta/Elev= 30
       0 2431.75     4.2 2430.55    14.7 2429.27      19 2429.44    27.6 2430.73
    38.1 2431.44    49.2 2432.85    53.5 2432.72    66.4 2433.33    79.4 2432.59
    83.7 2433.25      88 2432.59    96.6 2429.34   100.9 2429.09   105.2 2429.28
   109.5 2430.07   114.2 2430.33   123.5 2427.14   130.92425.713     138 2424.77
   146.7 2424.63   155.5 2424.95  157.62 2425.71   164.2  2429.3     173 2431.92
   184.2 2436.91   193.6 2438.83   225.4  2450.3   240.3 2457.74   249.1 2459.47
#Mann= 3 ,0,0
       0      .1       0   130.9    .045       0  157.62      .1       0
Bank Sta=130.9,157.62
XS Rating Curve= 0 ,0
Exp/Cntr(USF)=0,0
Exp/Cntr=0.3,0.1

Type RM Length L Ch R = 1 ,5723    ,151,152.7,154
XS GIS Cut Line= 3
2235707.15007764641037.4421800222235675.19609735640916.424978079
2235669.07725007640745.777125901
#Sta/Elev= 30
       0 2451.05    16.8 2441.27    27.3 2434.31    37.5 2428.89    41.6  2427.9
    54.1 2428.26    62.3  2429.6    78.9  2429.8    91.3 2431.62    99.6 2431.15
     112 2429.07   128.4 2430.75   137.9 2428.62   152.4 2422.89  154.87 2422.46
   164.4 2422.01   180.4 2422.44   184.4 2422.71   188.5 2424.37     196 2429.61
   200.5  2431.6   216.5 2435.14   231.7 2441.39   244.5  2441.9   248.5 2443.13
   258.7    2449   272.5 2452.67   276.5 2454.39   288.5 2461.15   295.9 2464.25
#Mann= 3 ,0,0
       0      .1       0  154.87    .045       0   180.4      .1       0
Bank Sta=154.87,180.4
XS Rating Curve= 0 ,0
Exp/Cntr(USF)=0,0
Exp/Cntr=0.3,0.1

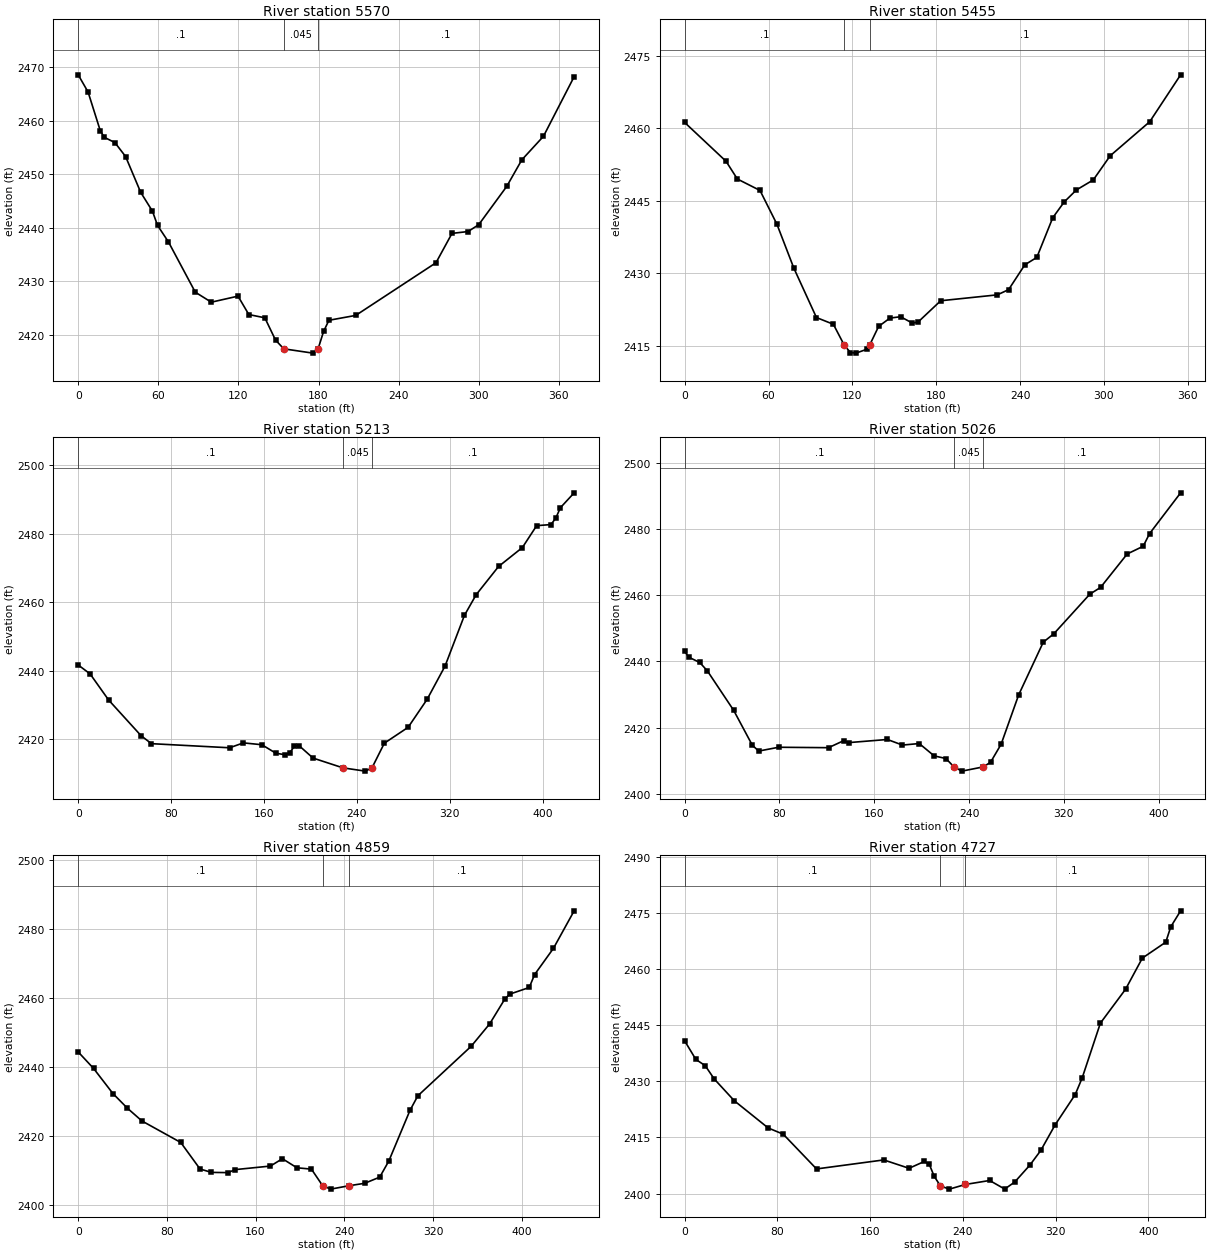
Type RM Length L Ch R = 1 ,5570    ,116.9,114.9,113.5
XS GIS Cut Line= 4
2235811.99605924641064.6065110422235821.32214869640936.839085554
2235830.64823814640754.9803412462235821.32214869 640694.36075981
#Sta/Elev= 30
       0 2468.62     7.4  2465.4    16.5  2458.2    19.5 2456.95    27.5 2455.95
    35.5 2453.35    46.8 2446.66    55.6 2443.14    59.4 2440.49    67.6 2437.39
    87.7    2428    99.7 2426.13   119.7 2427.26   127.8 2423.82   139.8 2423.21
   147.8 2419.05     1542417.413   175.8 2416.61   179.6 2417.33   183.8 2420.66
   187.8 2422.75   207.9 2423.66     268  2433.5     280 2438.99     292 2439.33
     300 2440.61     321 2447.77   332.3 2452.73   348.5 2457.13   371.5 2468.28
#Mann= 3 ,-1,0
       0      .1       0     154    .045       0   179.6      .1       0
Bank Sta=154,179.6
XS Rating Curve= 0 ,0
Exp/Cntr(USF)=0,0
Exp/Cntr=0.3,0.1

Type RM Length L Ch R = 1 ,5455    ,241.7,241.9,242.3
XS GIS Cut Line= 2
2235955.05068102641026.4835740422235903.57479294640675.382321188
#Sta/Elev= 30
       0  2461.2    29.6 2453.16    37.7 2449.49    53.9 2447.12      66 2440.13
    78.1 2431.04    94.3 2420.79   106.4  2419.4   114.22415.064   118.6 2413.55
   122.6 2413.42   130.7 2414.26   132.32415.041   138.8 2418.96   146.9 2420.68
   154.5 2420.96     163 2419.63   167.1 2419.88   183.2 2424.27   223.7 2425.49
   231.8 2426.57   243.4 2431.71     252 2433.25   263.4 2441.47   271.6 2444.74
   280.3 2447.22   292.4  2449.3   304.5  2454.3   332.8 2461.36   354.9 2471.07
#Mann= 3 ,-1,0
       0      .1       0   114.2    .045       0   132.3      .1       0
Bank Sta=114.2,132.3
XS Rating Curve= 0 ,0
Exp/Cntr(USF)=0,0
Exp/Cntr=0.3,0.1

Type RM Length L Ch R = 1 ,5213    ,176.4,186.9,194.9
XS GIS Cut Line= 3
2236166.59086694641051.3478565732236168.66333126640852.391281604
2236118.92418752640629.601366924
#Sta/Elev= 30
       0 2441.63    10.2 2439.04    26.2  2431.4    54.2 2420.96    63.1 2418.65
   130.4 2417.45   142.3 2418.88   158.2 2418.34   170.2 2415.87   178.2 2415.41
   182.2    2416   186.2 2417.88   190.2 2418.08   202.3 2414.44   228.12411.581
   247.3 2410.63  253.02 2411.56   263.7 2418.79   284.2 2423.43   300.6 2431.63
     316 2441.32   332.7 2456.13   342.8 2462.16   362.1  2470.4   382.6 2475.93
   394.9 2482.32   407.2 2482.64   411.3 2484.48   415.4 2487.58   427.2 2491.91
#Mann= 3 ,0,0
       0      .1       0   228.1    .045       0  253.02      .1       0
Bank Sta=228.1,253.02
XS Rating Curve= 0 ,0
Exp/Cntr(USF)=0,0
Exp/Cntr=0.3,0.1

Type RM Length L Ch R = 1 ,5026    ,169.1,167.7,167.9
XS GIS Cut Line= 3
2236247.41697552641084.5072857352236305.44597655640908.347818314
2236412.17788917640701.101386054
#Sta/Elev= 30
       0 2443.02     3.5 2441.26    12.7 2439.67    19.1 2437.15    41.3 2425.24
    57.1 2414.67    62.5 2412.91    79.3 2414.06   121.4 2413.93   134.1 2416.03
   138.3 2415.46   171.1 2416.41   183.8 2414.72     198 2415.18   210.6 2411.45
   220.5 2410.66   227.3 2408.12     234 2406.85   252.12408.135   258.2 2409.54
   267.1 2414.98   281.9 2429.88   302.7 2445.82   311.6 2448.34     342 2460.31
     351 2462.33   373.5 2472.44     387 2474.77   392.4 2478.59   418.6 2490.91
#Mann= 3 ,-1,0
       0      .1       0   227.3    .045       0   252.1      .1       0
Bank Sta=227.3,252.1
XS Rating Curve= 0 ,0
Exp/Cntr(USF)=0,0
Exp/Cntr=0.3,0.1

Type RM Length L Ch R = 1 ,4859    ,131.3,131.5,131
XS GIS Cut Line= 2
2236374.60587441641169.8833289422236554.04009166640760.088419453
#Sta/Elev= 30
       0  2444.3    13.9  2439.5    31.3 2432.23    44.4 2427.96    57.5 2424.26
    92.5 2418.02   109.9 2410.31   120.2 2409.33   135.3 2409.26   141.4 2410.13
   173.4 2411.17   184.2  2413.3   197.3 2410.67   210.4 2410.27   220.52405.466
   227.8 2404.47     244 2405.44   258.4 2406.16     272 2407.95   280.2 2412.63
   299.3 2427.34   306.4 2431.57   354.5 2445.95   371.2 2452.46     385 2459.74
   389.4  2461.1   406.9 2463.02   411.7 2466.76   428.7 2474.38   447.4 2485.28
#Mann= 3 ,-1,0
       0      .1       0   220.5    .045       0     244      .1       0
Bank Sta=220.5,244
XS Rating Curve= 0 ,0
Exp/Cntr(USF)=0,0
Exp/Cntr=0.3,0.1

Type RM Length L Ch R = 1 ,4727    ,221.8,229,224.6
XS GIS Cut Line= 3
2236508.16827068 641226.616868742236516.22785416641179.410736947
2236663.60309488640829.394540242
#Sta/Elev= 30
       0 2440.82     9.6 2435.87    17.7 2434.19    25.5 2430.63    42.8  2424.8
      72 2417.53      85 2415.86   113.7 2406.57   171.7 2408.98   193.5 2406.74
   206.6 2408.56   210.9 2407.84   215.2 2404.59   220.6    2402   228.3 2401.17
   242.12402.419     263 2403.48     276 2401.19   284.6 2403.06   297.7 2407.59
   307.1 2411.51   319.4 2418.32   336.8 2426.47   342.8 2430.91   358.5 2445.56
   380.2 2454.62   394.7 2462.96   414.9 2467.22   419.2 2471.32   427.7  2475.6
#Mann= 3 ,-1,0
       0      .1       0   220.6    .045       0   242.1      .1       0
Bank Sta=220.6,242.1
XS Rating Curve= 0 ,0
Exp/Cntr(USF)=0,0
Exp/Cntr=0.3,0.1

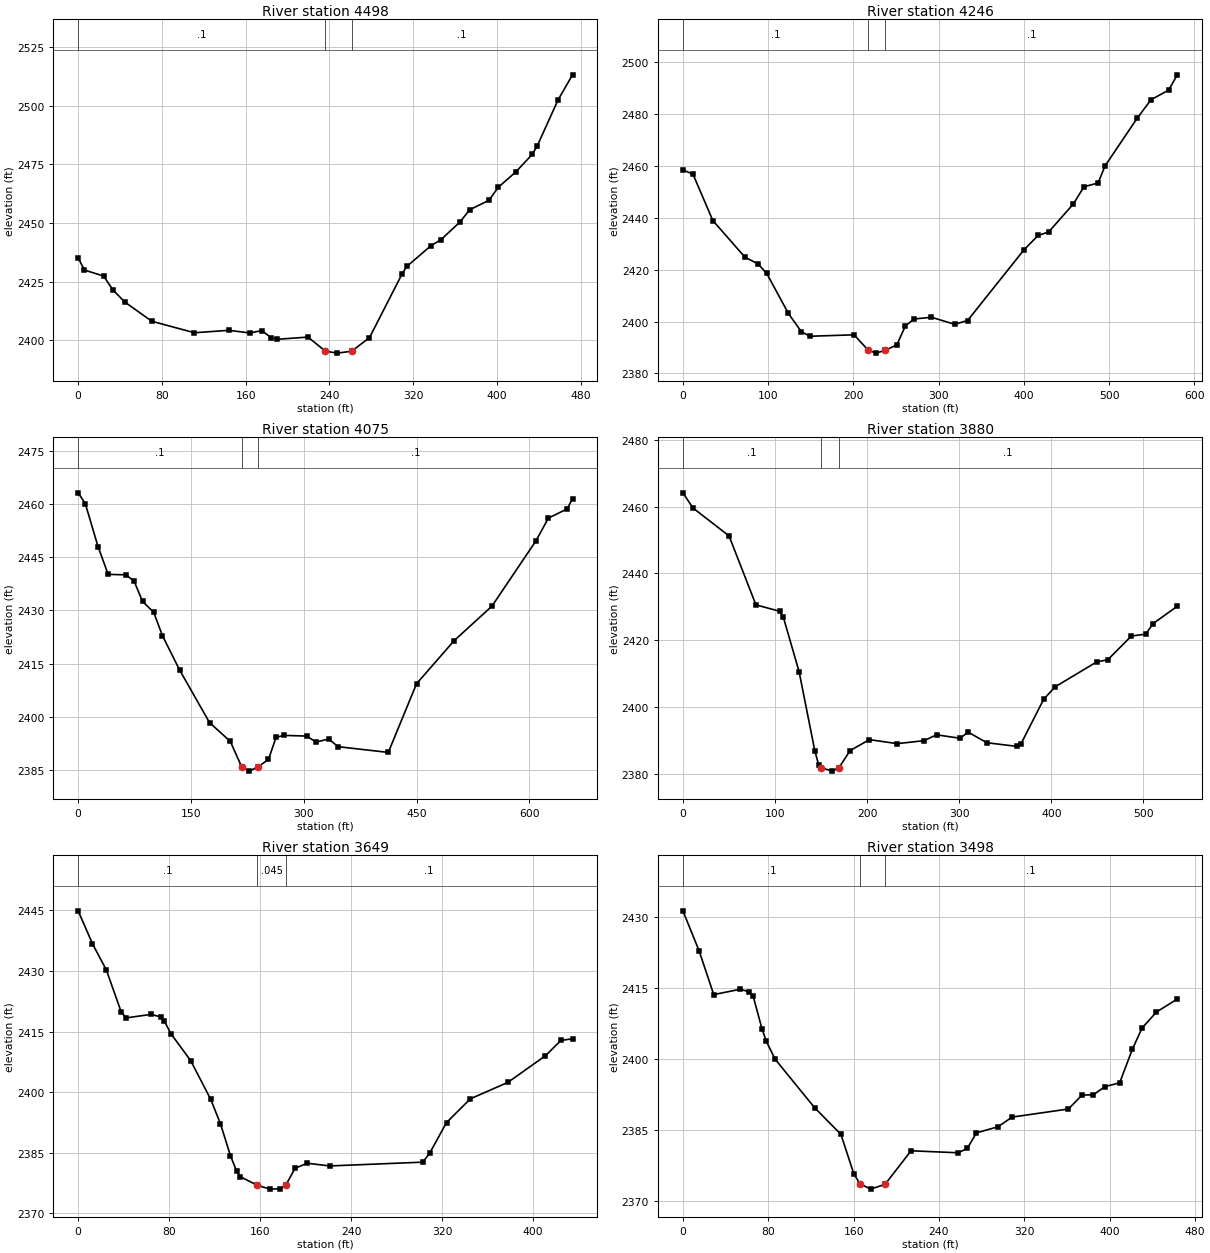
Type RM Length L Ch R = 1 ,4498    ,249,251.7,252.9
XS GIS Cut Line= 2
2236654.10943306641278.3558252592236886.94184461640867.700857632
#Sta/Elev= 30
       0 2435.14       6 2429.91    24.3 2427.34    33.5 2421.26    44.7 2416.21
    70.3 2408.06     111 2403.14   143.9 2404.17   163.8 2403.06   175.5 2404.06
   184.3 2401.02   189.9 2400.34   219.5 2401.29   236.12395.277   247.5 2394.44
   261.22395.269   278.2 2401.03   309.4  2428.3     314  2431.5     337 2440.33
   346.2 2442.78   364.6 2450.39   373.8 2455.61   392.2 2459.66   401.4 2465.33
   417.8 2471.72   433.6 2479.29   438.2 2482.71   458.3 2502.55   472.1 2513.25
#Mann= 3 ,-1,0
       0      .1       0   236.1    .045       0   261.2      .1       0
Bank Sta=236.1,261.2
XS Rating Curve= 0 ,0
Exp/Cntr(USF)=0,0
Exp/Cntr=0.3,0.1

Type RM Length L Ch R = 1 ,4246    ,170.9,171,170.8
XS GIS Cut Line= 3
2236828.16552441641402.4442376312237025.10613278641151.705227767
2237091.64940112640899.337408847
#Sta/Elev= 30
       0 2458.34    11.8 2456.76    35.1 2438.89    72.8 2424.76    88.1 2422.21
    98.2 2418.59   123.7 2403.14   138.9  2396.1   149.1 2394.34   200.8 2394.89
   217.32388.955   226.7 2387.84   237.4 2388.97   250.8 2390.98     261 2398.32
   271.2 2400.98   291.5 2401.65   318.8 2398.94   333.9  2400.4     400 2427.61
   416.6 2433.14     429  2434.5     458 2445.29   470.4  2451.9   486.9 2453.33
   495.2 2459.97   532.9 2478.34     549 2485.38   569.7 2489.11   579.8 2494.98
#Mann= 3 ,-1,0
       0      .1       0   217.3    .045       0   237.4      .1       0
Bank Sta=217.3,237.4
XS Rating Curve= 0 ,0
Exp/Cntr(USF)=0,0
Exp/Cntr=0.3,0.1

Type RM Length L Ch R = 1 ,4075    ,206.8,195.6,185.7
XS GIS Cut Line= 3
2236962.42048352641508.6296388812237135.12584373641287.310918011
2237242.58695676640926.548610003
#Sta/Elev= 30
       0 2463.21     9.5 2460.18    26.5 2447.98    39.9 2440.18    63.6 2440.04
    74.4 2438.27    85.6 2432.53   100.4 2429.47     112  2422.9   134.8  2413.2
   174.7  2398.3   202.3 2392.99   217.32385.852   227.6  2384.6   239.3 2385.84
     253 2387.89   263.1 2394.13   273.3  2394.7   303.8  2394.5   316.3  2392.8
     333 2393.67   345.6 2391.51   412.3 2389.88   449.9  2409.3     500 2421.49
   550.1  2431.2   608.5 2449.62   625.2 2456.08   650.2 2458.68   657.2 2461.56
#Mann= 3 ,-1,0
       0      .1       0   217.3    .045       0   239.3      .1       0
Bank Sta=217.3,239.3
XS Rating Curve= 0 ,0
Exp/Cntr(USF)=0,0
Exp/Cntr=0.3,0.1

Type RM Length L Ch R = 1 ,3880    ,231.5,231.1,231
XS GIS Cut Line= 3
2237342.15907827641507.5320061372237233.35470133641213.242072327
2237282.05761291640995.633318453
#Sta/Elev= 30
       0 2464.14      11 2459.59    50.1 2451.24    79.3 2430.59   104.9 2428.68
   109.1 2426.87   126.2 2410.55   143.2 2386.94   147.5 2382.59   149.7 2381.85
   162.2  2380.8   169.52381.841   181.6 2386.96   202.6 2390.23   232.8 2389.03
   261.8 2389.92   275.4 2391.68     301 2390.64   309.6 2392.48   330.2  2389.3
   363.1 2388.19   367.1 2388.96   391.7 2402.29     404 2406.01   449.1 2413.47
   461.4 2414.16     487 2421.27   502.4  2421.8   510.6 2424.99   536.8 2430.17
#Mann= 3 ,-1,0
       0      .1       0   149.7    .045       0   169.5      .1       0
Bank Sta=149.7,169.5
XS Rating Curve= 0 ,0
Exp/Cntr(USF)=0,0
Exp/Cntr=0.3,0.1

Type RM Length L Ch R = 1 ,3649    ,147.7,150.3,152.1
XS GIS Cut Line= 4
2237553.17964406641395.9205620822237525.51062232641331.813896858
2237438.77799042641135.9660183722237373.66491915640999.960968002
#Sta/Elev= 30
       0 2444.91    12.6 2436.77    24.8 2430.27    37.8 2419.94    42.2  2418.4
      64 2419.26    72.7 2418.65    75.9 2417.58    81.5 2414.53      99  2407.8
   116.5 2398.29   125.2 2392.17     134 2384.25   139.5 2380.37   142.7 2379.07
   157.62376.945   168.9    2376   177.7  2376.1   182.5 2376.92   190.8 2381.17
   201.5 2382.41   221.3 2381.74   303.1 2382.68   309.1 2384.87     324 2392.49
     345 2398.37     378 2402.44     411 2409.03   424.6 2412.83   434.8 2413.22
#Mann= 3 ,-1,0
       0      .1       0   157.6    .045       0   182.5      .1       0
Bank Sta=157.6,182.5
XS Rating Curve= 0 ,0
Exp/Cntr(USF)=0,0
Exp/Cntr=0.3,0.1

Type RM Length L Ch R = 1 ,3498    ,133.5,133.5,133.9
XS GIS Cut Line= 4
2237669.01604186641369.2554679622237625.18342143641185.531505762
2237589.74428152641094.1358291342237472.23555442640962.637967864
#Sta/Elev= 30
       0  2431.4    15.2 2422.94    28.9  2413.7    53.5 2414.82    61.8 2414.33
    65.9 2413.34    74.1 2406.48    78.2 2403.83    86.4 2400.06   123.4 2389.81
   148.1 2384.17   160.1 2375.89   165.92373.737     176  2372.6   189.5 2373.62
   213.8  2380.7   257.9 2380.28   266.5 2381.19   275.1 2384.49   295.3 2385.77
   308.5 2387.82   361.3 2389.53     374 2392.47   384.7 2392.53   395.5 2394.26
   409.3 2395.06   421.3  2402.2   430.3 2406.63   443.8 2410.02   463.3 2412.76
#Mann= 3 ,-1,0
       0      .1       0   165.9    .045       0   189.5      .1       0
Bank Sta=165.9,189.5
XS Rating Curve= 0 ,0
Exp/Cntr(USF)=0,0
Exp/Cntr=0.3,0.1