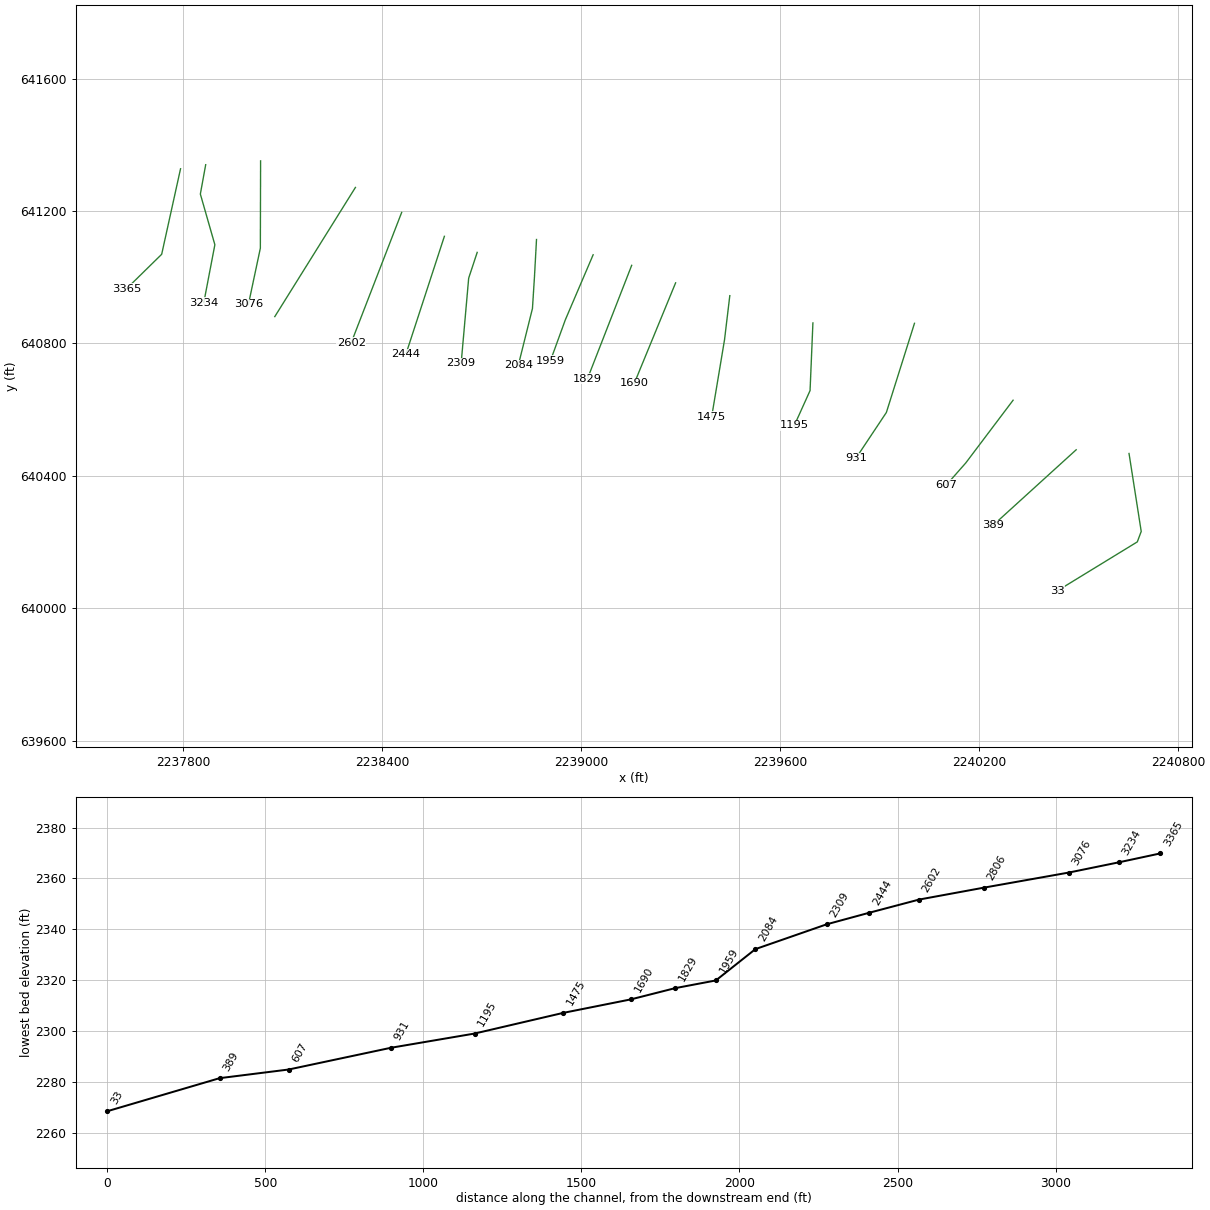
HEC-RAS study SCHOOLCRN.prj: SCHOOLCRN

--- SCHOOLCRN.g01 (geometry) --- (continued)

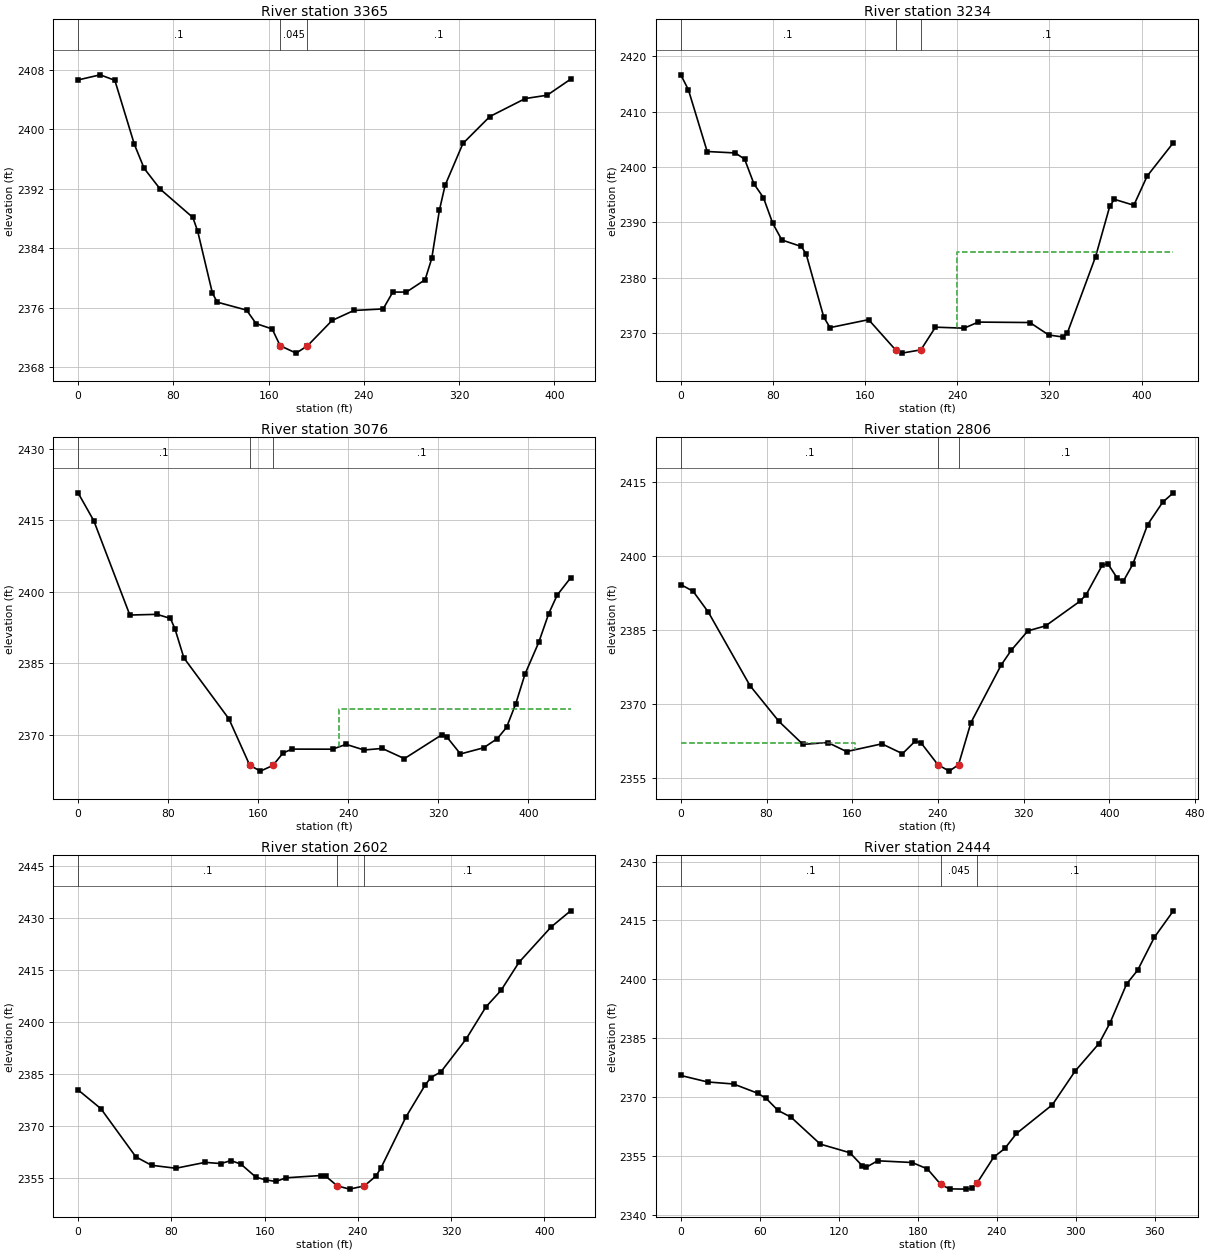
Type RM Length L Ch R = 1 ,3365    ,125.8,130.9,136.8
XS GIS Cut Line= 3
2237792.22299264641327.3352133282237735.33384699641069.002535515
2237629.01642724640964.550333656
#Sta/Elev= 30
       0 2406.68    18.6 2407.37    30.9 2406.63    47.3 2397.99    55.5 2394.76
      69 2391.96    96.4 2388.14   100.5 2386.26   112.8 2377.95   116.9 2376.72
   141.5 2375.65   149.5 2373.83     163 2373.11   169.72370.851   183.1 2369.85
   192.62370.827   213.3 2374.25   231.6  2375.6   256.2 2375.81   264.3 2378.08
   275.7 2378.08   291.4 2379.74     297 2382.61   303.4 2389.09   308.2 2392.47
   323.2 2398.12   345.8 2401.75   375.5 2404.17   393.9 2404.62   413.6 2406.78
#Mann= 3 ,-1,0
       0      .1       0   169.7    .045       0   192.6      .1       0
Bank Sta=169.7,192.6
XS Rating Curve= 0 ,0
Exp/Cntr(USF)=0,0
Exp/Cntr=0.3,0.1

Type RM Length L Ch R = 1 ,3234    ,160.4,157.8,154.6
XS GIS Cut Line= 4
2237868.06472635641339.676796602 2237851.9455594641251.021378357
2237895.69758399641097.8892922962237862.30788101640922.881193941
#Sta/Elev= 30
       0 2416.66     6.6 2413.96    22.9  2402.8    47.3 2402.54    55.4 2401.42
    63.5 2396.95    71.7 2394.47    79.8 2389.82    87.7 2386.81   104.5 2385.64
   108.7 2384.35   124.1 2372.86   129.5 2370.97     163 2372.41   186.42366.946
   191.9 2366.36   208.42366.953     221 2371.05   245.9 2370.87   258.2 2371.97
     303 2371.89   319.3 2369.64   331.5 2369.28   335.6 2370.06     360 2383.79
   372.3  2392.9   376.3 2394.16   393.2 2393.09   404.8 2398.37   427.5 2404.39
#Mann= 3 ,-1,0
       0      .1       0   186.4    .045       0   208.4      .1       0
#XS Ineff= 2 , 0
                          239.68         2384.72
Permanent Ineff=
       F       F
Bank Sta=186.4,208.4
XS Rating Curve= 0 ,0
Exp/Cntr(USF)=0,0
Exp/Cntr=0.3,0.1

Type RM Length L Ch R = 1 ,3076    ,273.5,270.5,260.7
XS GIS Cut Line= 3
2238033.57509409641351.146758626 2238032.8348212641087.392458131
2237996.82373214640917.499479125
#Sta/Elev= 30
       0 2420.71      14 2414.85      46 2395.08      70 2395.23      82 2394.38
      86 2392.23      94 2386.09     134  2373.3   152.5 2363.56     162 2362.35
   173.12363.554     182 2366.14     190 2366.97     226 2366.95     238 2367.97
     254 2366.78   270.1 2367.11   289.8 2364.97   323.3 2370.01   327.4 2369.54
   339.6 2365.95   360.1 2367.24   372.3 2369.16   380.5 2371.52   388.7 2376.48
   396.9 2382.69   409.1 2389.35     418  2395.4   425.5 2399.27   437.4 2402.87
#Mann= 3 ,-1,0
       0      .1       0   152.5    .045       0   173.1      .1       0
#XS Ineff= 2 , 0
                          231.77         2375.48
Permanent Ineff=
       F       F
Bank Sta=152.5,173.1
XS Rating Curve= 0 ,0
Exp/Cntr(USF)=0,0
Exp/Cntr=0.3,0.1

Type RM Length L Ch R = 1 ,2806    ,202.4,204.1,206.2
XS GIS Cut Line= 2
2238319.44485483 641270.963015012238076.37805156640880.776830816
#Sta/Elev= 30
       0 2394.19    11.5 2392.83    25.7  2388.6    64.6  2373.7    91.6 2366.46
     114  2361.8   137.2 2362.18   154.7 2360.34   187.7 2361.91   206.9 2359.91
   218.9 2362.49   224.4 2362.06     2402357.674   250.5 2356.38   259.2 2357.67
   270.8 2366.22     299 2377.88   308.4 2380.87   323.9  2384.8   340.5 2385.82
   372.4 2390.79   378.3 2392.13   393.3  2398.1   398.6  2398.4   407.4 2395.46
   413.1 2394.91   421.8 2398.27   435.7 2406.34   449.8 2410.89   459.7 2412.78
#Mann= 3 ,-1,0
       0      .1       0     240    .045       0   259.2      .1       0
#XS Ineff= 2 , 0
          162.86 2362.04
Permanent Ineff=
       F       F
Bank Sta=240,259.2
XS Rating Curve= 0 ,0
Exp/Cntr(USF)=0,0
Exp/Cntr=0.3,0.1

Type RM Length L Ch R = 1 ,2602    ,156.8,157.5,158.2
XS GIS Cut Line= 2
2238458.88844197641195.4843761012238306.65186518640801.460295013
#Sta/Elev= 30
       0 2380.35    19.6 2374.92    49.6 2361.02      63  2358.6    83.9 2357.74
     109 2359.44   122.5 2359.09   131.1 2359.95   139.7 2358.93   152.6 2355.14
   161.1 2354.38   169.7 2353.93   178.3 2354.98   208.3 2355.65   212.6 2355.39
   222.32352.655   232.8 2351.72   245.52352.643   255.5  2355.5   259.8 2357.85
   281.2 2372.53   297.7 2381.77   302.6  2383.9   311.2 2385.55   332.7 2394.96
   349.8 2404.28   362.7 2409.03   378.1 2417.12   405.6  2427.3   422.4 2431.99
#Mann= 3 ,-1,0
       0      .1       0   222.3    .045       0   245.5      .1       0
Bank Sta=222.3,245.5
XS Rating Curve= 0 ,0
Exp/Cntr(USF)=0,0
Exp/Cntr=0.3,0.1

Type RM Length L Ch R = 1 ,2444    ,130.7,134.7,138
XS GIS Cut Line= 2
2238587.65658955641123.3185000532238471.73147544640767.451030958
#Sta/Elev= 30
       0  2375.5    20.3 2373.85    40.1 2373.33    58.4 2370.98    64.8 2369.68
    73.8 2366.62    83.8 2364.86     106 2358.02   128.5 2355.82   137.7 2352.56
   141.1 2352.14   149.5 2353.77   175.8 2353.33   187.4  2351.7   197.6 2347.73
   204.2 2346.61   216.8 2346.55     221 2346.75   225.2 2348.11   237.8  2354.7
   246.2  2356.9   255.1 2360.72   282.4 2368.05   299.6 2376.59   317.8 2383.64
   326.2  2388.9   338.8 2398.82   347.2 2402.33   359.8 2410.65   374.3 2417.44
#Mann= 3 ,-1,0
       0      .1       0   197.6    .045       0   225.2      .1       0
Bank Sta=197.6,225.2
XS Rating Curve= 0 ,0
Exp/Cntr(USF)=0,0
Exp/Cntr=0.3,0.1

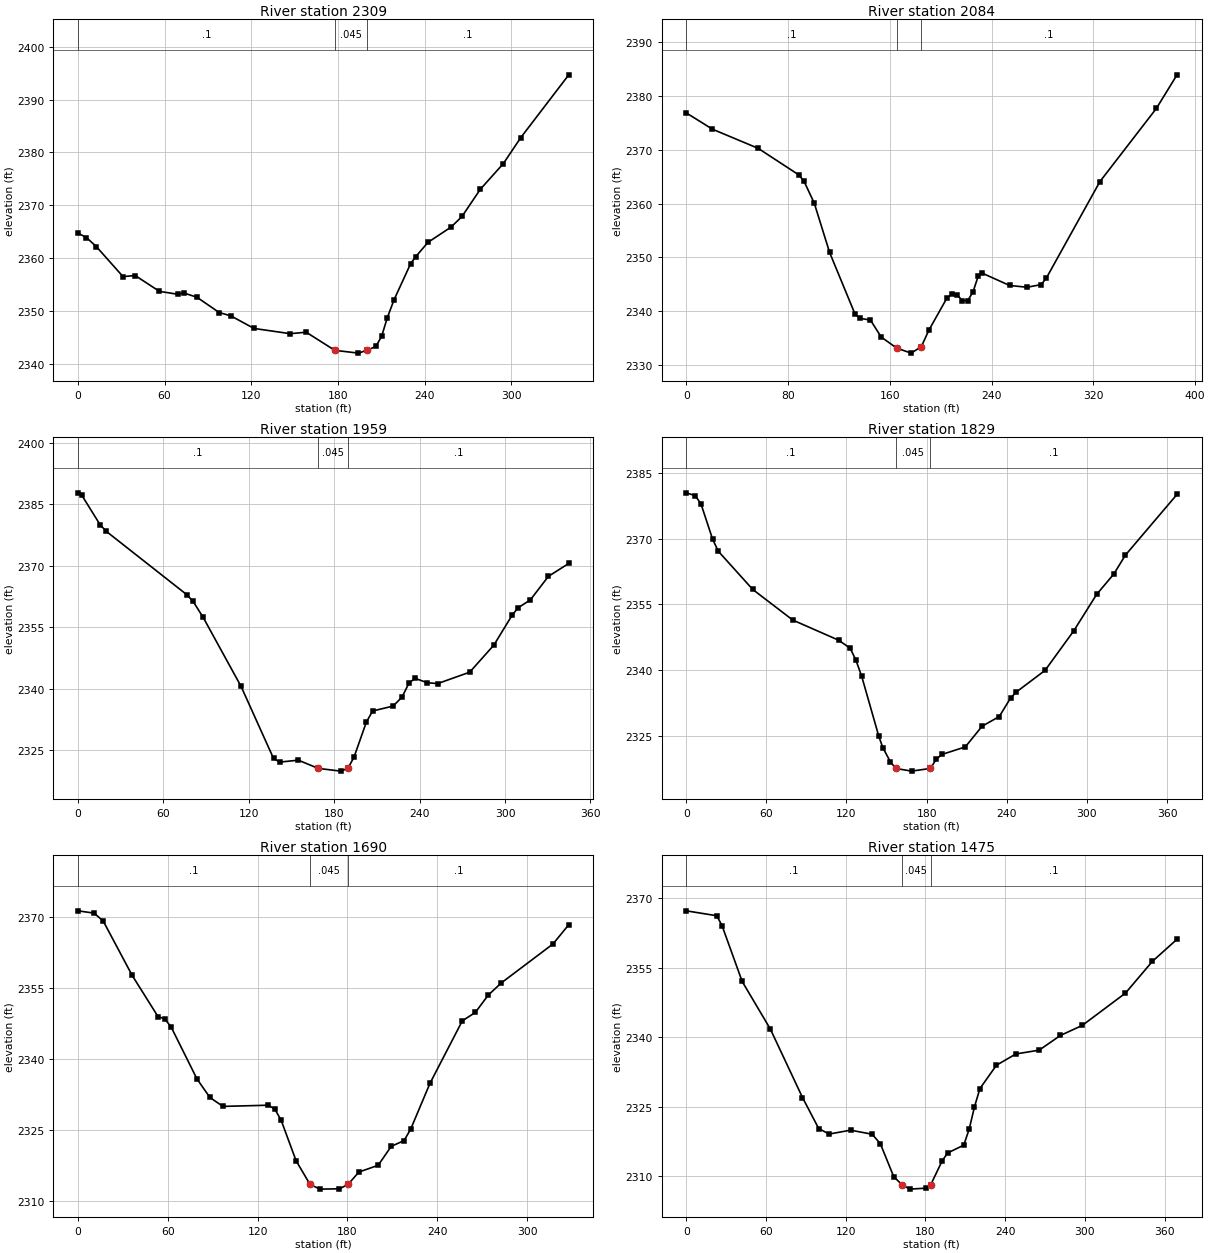
Type RM Length L Ch R = 1 ,2309    ,218.7,225.6,224.4
XS GIS Cut Line= 3
2238686.59654744641074.7724417082238660.91249709640996.964877413
2238638.25009972640740.124373912
#Sta/Elev= 30
       0 2364.73     5.9 2363.87    12.7 2362.18    31.2 2356.49    39.6  2356.7
    56.4  2353.7    69.1 2353.15    73.3  2353.4    82.4 2352.58    97.8 2349.69
   105.8 2349.07   121.9 2346.68     147 2345.69     158 2345.97   177.8 2342.54
   194.2 2342.01  200.05 2342.55   206.2 2343.27   210.2 2345.16   214.2 2348.74
   218.9 2352.15   230.3 2358.93   233.7 2360.22   242.3 2362.97   258.4 2365.89
   265.9 2367.88   278.5    2373   294.5 2377.88   306.6 2382.81   339.8 2394.68
#Mann= 3 ,0,0
       0      .1       0   177.8    .045       0  200.05      .1       0
Bank Sta=177.8,200.05
XS Rating Curve= 0 ,0
Exp/Cntr(USF)=0,0
Exp/Cntr=0.3,0.1

Type RM Length L Ch R = 1 ,2084    ,126.2,125.2,118.3
XS GIS Cut Line= 4
2238865.41797094641113.7139945182238859.31577273641002.069703747
2238853.19692544640905.3919165752238810.46921145640733.506953881
#Sta/Elev= 30
       0 2376.83    20.6  2373.8    56.6 2370.24    88.7 2365.29    92.7  2364.1
   100.7 2360.05   112.7 2350.94   132.7  2339.5   136.8  2338.7   144.8  2338.4
   153.3 2335.24   165.42333.201   176.8 2332.26   184.8 2333.45   190.7  2336.5
   204.9 2342.46   208.9 2343.26     213 2343.06   217.1 2341.99   221.3 2342.02
   225.4 2343.59   229.5 2346.53   232.8 2347.08   254.2 2344.81   267.9 2344.48
     279 2344.97   283.1 2346.19   325.2 2364.08   369.6 2377.66   385.8 2383.88
#Mann= 3 ,-1,0
       0      .1       0   165.4    .045       0   184.8      .1       0
Bank Sta=165.4,184.8
XS Rating Curve= 0 ,0
Exp/Cntr(USF)=0,0
Exp/Cntr=0.3,0.1

Type RM Length L Ch R = 1 ,1959    ,128.6,129.3,130.2
XS GIS Cut Line= 3
2239036.15045939641067.5413697432238952.32225153640871.126371755
2238907.53225938640747.723831163
#Sta/Elev= 30
       0 2387.79     2.6 2387.25    15.6 2379.99      20 2378.37    76.5 2362.95
    80.9 2361.32      88  2357.4   114.6 2340.59   137.4 2323.04   141.7 2322.15
   154.8 2322.62  168.84 2320.61   184.7 2319.95   189.6 2320.62   193.9 2323.33
   202.6  2331.9     207 2334.61   221.4 2335.81   227.7 2338.01   232.6 2341.47
   236.9 2342.56   245.4  2341.5   252.7 2341.29   275.2 2344.07   292.2 2350.68
     305 2357.96   309.2 2359.77   317.8 2361.69   330.5 2367.43   344.8 2370.58
#Mann= 3 ,0,0
       0      .1       0  168.84    .045       0   189.6      .1       0
Bank Sta=168.84,189.6
XS Rating Curve= 0 ,0
Exp/Cntr(USF)=0,0
Exp/Cntr=0.3,0.1

Type RM Length L Ch R = 1 ,1829    ,140,139.7,139.4
XS GIS Cut Line= 2
2239152.32336704641035.5920591522239019.05917319640693.110296167
#Sta/Elev= 30
       0 2380.49     6.9 2379.83    11.2 2377.83    19.8 2369.86    24.1 2367.12
    49.8 2358.42    79.8 2351.42   114.2 2346.81   122.8 2344.98   127.1 2342.24
   131.4 2338.57   144.2 2324.88   147.2 2322.28   152.8 2319.08   156.9 2317.52
   168.8 2316.91   182.9 2317.53   187.2 2319.62   191.4 2320.71     209 2322.45
   221.5 2327.16   234.4 2329.38   242.9 2333.62   247.2 2334.99   268.7 2339.93
   290.2 2348.97   307.3 2357.28   320.2 2361.95   328.8 2366.24   367.5 2380.13
#Mann= 3 ,0,0
       0      .1       0   156.9    .045       0   182.9      .1       0
Bank Sta=156.9,182.9
XS Rating Curve= 0 ,0
Exp/Cntr(USF)=0,0
Exp/Cntr=0.3,0.1

Type RM Length L Ch R = 1 ,1690    ,211.6,214.6,217
XS GIS Cut Line= 2
2239284.73013018 640982.704503712239160.31356863640679.481626931
#Sta/Elev= 30
       0 2371.38    10.8 2370.89    16.9  2369.2    36.2 2357.72    53.5 2348.99
    57.9 2348.54    62.2 2346.82    79.5 2335.81    88.1 2331.91    96.8 2330.01
     127 2330.26   131.4 2329.48   135.7 2327.08   145.7  2318.5     155 2313.51
   161.6 2312.51   174.6 2312.58   180.42313.508   187.6 2316.12   200.5 2317.55
   209.2 2321.55   217.8 2322.78   222.2 2325.19   235.1 2334.89   256.7 2348.11
   265.4 2349.89     274 2353.54   282.7 2356.12   317.3 2364.38   327.8 2368.45
#Mann= 3 ,-1,0
       0      .1       0     155    .045       0   180.4      .1       0
Bank Sta=155,180.4
XS Rating Curve= 0 ,0
Exp/Cntr(USF)=0,0
Exp/Cntr=0.3,0.1

Type RM Length L Ch R = 1 ,1475    ,276.7,279.8,279.7
XS GIS Cut Line= 3
2239448.16321593640944.0369824952239432.21560297640810.580642441
2239393.60559264 640578.92058046
#Sta/Elev= 30
       0 2367.32      23 2366.26      27 2364.09    42.1 2352.06    63.3 2341.78
    87.5 2326.98    99.7 2320.28   107.6 2319.09   123.7 2319.93   139.9 2319.05
   146.1 2316.99   156.1 2309.91   162.3 2308.15   168.3 2307.19   180.4  2307.4
     1842308.155   192.6  2313.3   196.7    2315   208.8 2316.69   212.9 2320.13
   216.9 2324.97     221 2328.92   233.4 2333.95     248 2336.39   265.6 2337.22
   281.6  2340.4     298 2342.56   330.5 2349.54   350.8 2356.41   369.3 2361.18
#Mann= 3 ,-1,0
       0      .1       0   162.3    .045       0     184      .1       0
Bank Sta=162.3,184
XS Rating Curve= 0 ,0
Exp/Cntr(USF)=0,0
Exp/Cntr=0.3,0.1

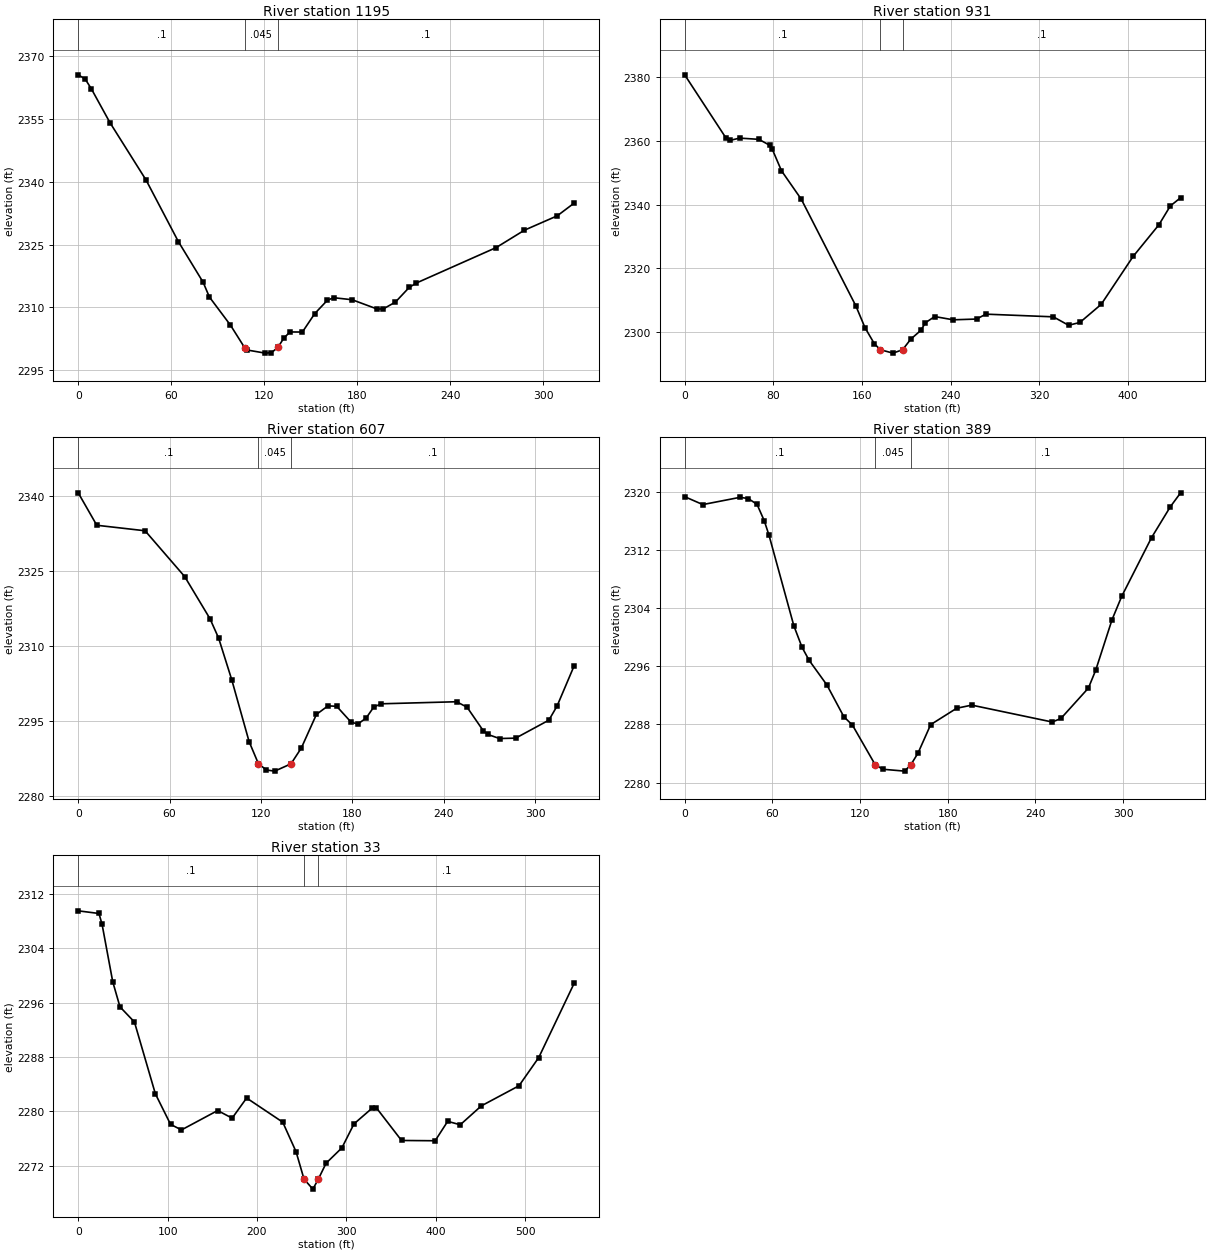
Type RM Length L Ch R = 1 ,1195    ,266.5,263.9,261.4
XS GIS Cut Line= 3
2239698.73125181640861.687251381 2239690.1060911640657.259053826
2239642.71319433640552.122750056
#Sta/Elev= 30
       0 2365.61     4.5  2364.6     8.5 2362.25    20.5 2354.17    43.8 2340.44
    64.6 2325.75    80.6 2316.01    84.6 2312.51    98.2 2305.78   107.32300.426
   108.6 2299.86   120.6 2299.09   124.6  2299.2   128.82300.447   132.6 2302.67
   136.6 2304.15   144.6 2304.13   152.6 2308.55   160.7 2311.72   164.7 2312.34
   176.7 2311.85   192.7 2309.65   196.7 2309.64   204.6 2311.29   213.5 2314.79
   217.9 2315.81   269.6 2324.32   287.8 2328.47     309 2331.91   319.9 2334.95
#Mann= 3 ,-1,0
       0      .1       0   107.3    .045       0   128.8      .1       0
Bank Sta=107.3,128.8
XS Rating Curve= 0 ,0
Exp/Cntr(USF)=0,0
Exp/Cntr=0.3,0.1

Type RM Length L Ch R = 1 ,931     ,326.5,324,319.7
XS GIS Cut Line= 3
2240004.92159642 640860.50839323 2239920.1474433 640591.07766897
2239828.65850578640453.424588662
#Sta/Elev= 30
       0 2380.56      37 2360.95    41.2 2360.08    49.6 2360.77      67 2360.38
    76.6 2358.56      79 2357.35    87.4 2350.55   105.3 2341.63   154.5 2308.31
   162.8 2301.47   171.2 2296.47   176.62294.592     188 2293.52   196.72294.573
   204.2 2297.93   213.2 2300.64   217.3 2303.02   225.7 2304.96   242.4 2303.94
   263.5 2304.18   271.9 2305.71   332.8 2304.87   346.6 2302.23   356.8 2303.12
     376 2308.77   404.8 2323.75   428.1 2333.66   438.4 2339.55   447.7 2342.13
#Mann= 3 ,-1,0
       0      .1       0   176.6    .045       0   196.7      .1       0
Bank Sta=176.6,196.7
XS Rating Curve= 0 ,0
Exp/Cntr(USF)=0,0
Exp/Cntr=0.3,0.1

Type RM Length L Ch R = 1 ,607     ,220.8,218.5,216.6
XS GIS Cut Line= 3
2240302.23771894640628.2266201652240159.66500046640438.880080101
2240101.18731575 640372.35430583
#Sta/Elev= 30
       0 2340.56    12.2 2334.08    43.9 2332.98    69.9 2323.83    86.5 2315.42
    92.2 2311.53   100.8 2303.22   112.2 2290.86   118.32286.454   123.6 2285.19
     129 2284.97   139.72286.427   146.5  2289.6   156.4  2296.3     164 2298.01
   169.7 2297.92   179.1 2294.77   183.6 2294.37   189.1  2295.6   194.1  2297.8
   199.1 2298.42   248.4 2298.83   255.3 2297.74   265.9 2293.05     269 2292.29
   276.6 2291.48   287.2 2291.56     309 2295.15   314.4 2297.98   325.6 2306.01
#Mann= 3 ,-1,0
       0      .1       0   118.3    .045       0   139.7      .1       0
Bank Sta=118.3,139.7
XS Rating Curve= 0 ,0
Exp/Cntr(USF)=0,0
Exp/Cntr=0.3,0.1

Type RM Length L Ch R = 1 ,389     ,348.1,355.5,358.5
XS GIS Cut Line= 2
2240492.37013296640478.475961709 2240241.4973941640250.038996243
#Sta/Elev= 30
       0 2319.41    12.4 2318.32    37.9 2319.32    43.5 2319.15    49.5 2318.35
    54.4 2316.11    57.7 2314.09    74.7  2301.6    80.3 2298.64    85.1 2296.86
    97.3 2293.45   108.9 2289.07   114.8 2287.91   130.32282.468   135.5 2281.83
   150.5 2281.57   154.82282.477   159.6 2284.04   168.3 2287.98   186.1 2290.24
   196.4 2290.67   251.5 2288.34   257.4 2288.83   276.2 2293.02   281.2 2295.48
   292.4 2302.46     299 2305.67   319.4 2313.76   332.3 2318.03   339.3 2319.94
#Mann= 3 ,-1,0
       0      .1       0   130.3    .045       0   154.8      .1       0
Bank Sta=130.3,154.8
XS Rating Curve= 0 ,0
Exp/Cntr(USF)=0,0
Exp/Cntr=0.3,0.1

Type RM Length L Ch R = 1 ,33      ,,,
XS GIS Cut Line= 4
2240651.74654602640467.2874636392240688.50171336640231.859835281
2240676.68121385640200.2866589512240435.57503001640052.455490867
#Sta/Elev= 30
       0 2309.48    23.2 2309.09    26.7 2307.49    38.6 2299.07    46.7 2295.37
    62.9 2293.14    86.3 2282.59   103.3  2278.1   115.5 2277.28     156 2280.13
   172.2 2279.01   188.4 2281.97   228.8 2278.42   243.7 2274.08   252.62270.052
   262.5 2268.58   268.72270.072   277.3 2272.39     295 2274.65   308.5 2278.17
   328.9 2280.49   333.6 2280.52   361.7 2275.73   399.3 2275.69   413.3 2278.54
   427.4 2278.04   450.9 2280.81   493.1 2283.77   515.2 2287.92   554.8 2298.83
#Mann= 3 ,-1,0
       0      .1       0   252.6    .045       0   268.7      .1       0
Bank Sta=252.6,268.7
XS Rating Curve= 0 ,0
Exp/Cntr(USF)=0,0
Exp/Cntr=0.3,0.1
LCMann Table=0

Chan Stop Cuts=-1
Use User Specified Reach Order=0
Composite Channel Slope=5